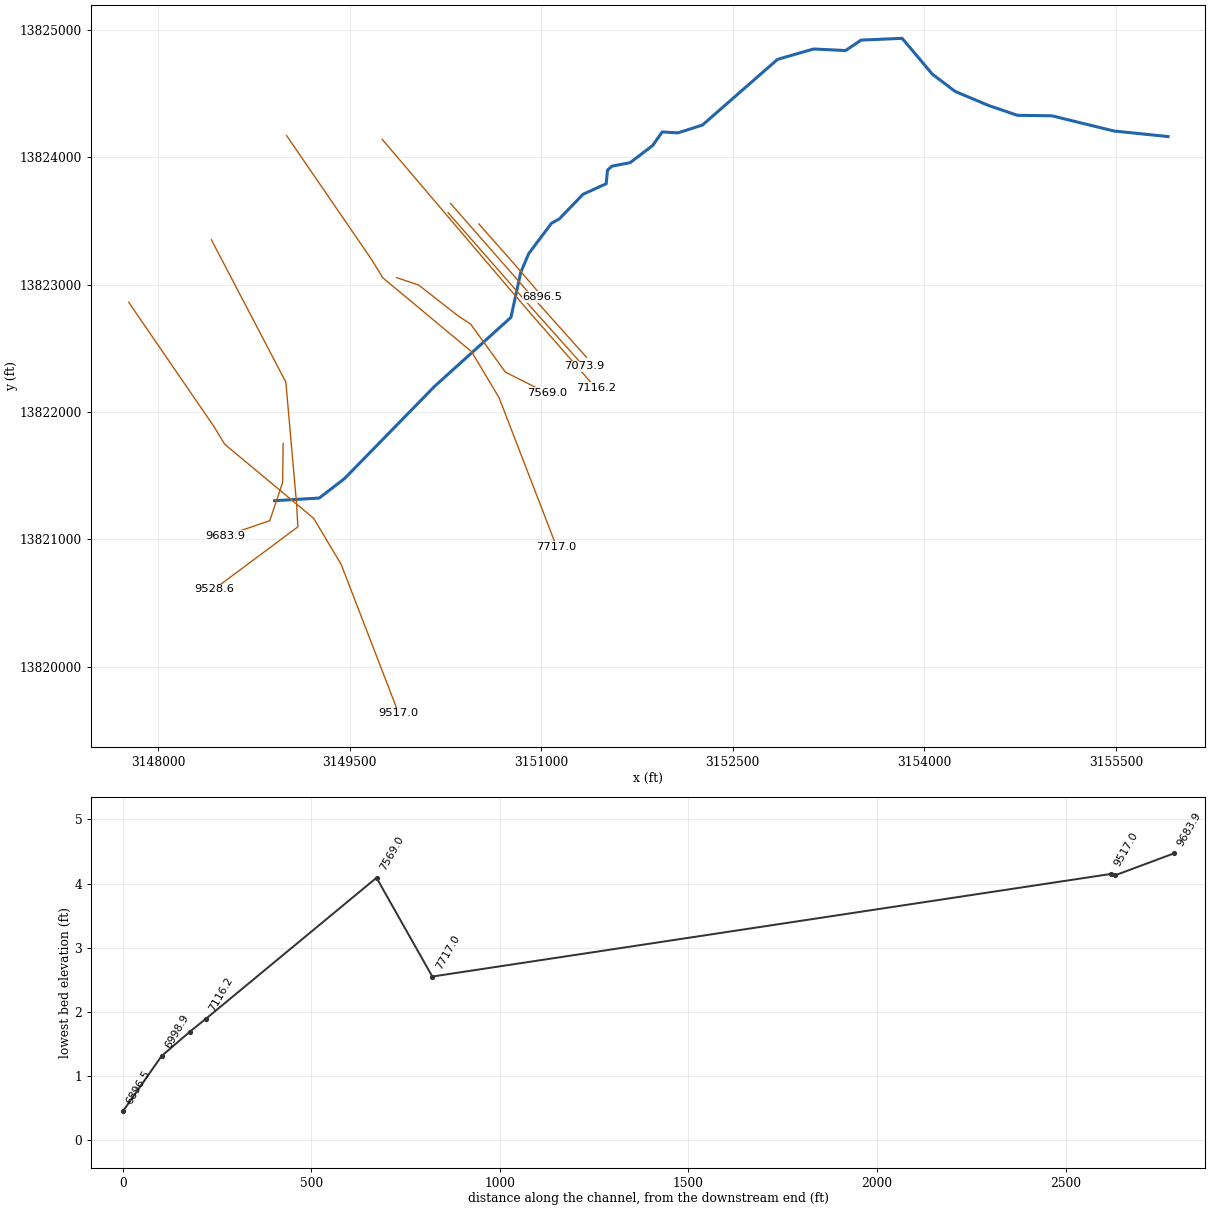
--- C102-00-00.PRJ (project) ---

Proj Title=C102-00-00
Current Plan=p02
Default Exp/Contr=0.3,0.1
English Units
Geom File=g01
Flow File=f01
Flow File=f02
Plan File=p01
Plan File=p02
Y Axis Title=Elevation
X Axis Title(PF)=Main Channel Distance
X Axis Title(XS)=Station
BEGIN DESCRIPTION:
Sims Bayou Watershed
Plum Creek
HCFCD Unit C102-00-00
Flood Hazard Model
10, 2, 1, 0.2% Event
Filename C102-00-00.prj
Prepared by:  Watershed Concepts  Date:
Reviewed by:                      Date:
STATUS FINAL
END DESCRIPTION:
DSS Export Rating Curves= 0
DSS Export Rating Curve Sorted= 0
DSS Export Volume Flow Curves= 0
DXF OffsetX= 0
DXF OffsetY= 0
DXF ScaleX= 1
DXF ScaleY= 10

--- C102-00-00.p02 (plan) ---

Plan Title=Effective Floodway 2015
Program Version=4.10
Short Identifier=Eff+RiskMAP FW
Geom File=g01
Flow File=f02
Subcritical Flow
K Sum by GR= 0
Std Step Tol= 0.01
Critical Tol= 0.01
Num of Std Step Trials= 20
Max Error Tol= 0.3
Flow Tol Ratio= 0.001
Split Flow NTrial= 30
Split Flow Tol= 0.02
Split Flow Ratio= 0.02
Log Output Level= 0
Friction Slope Method= 1
Unsteady Friction Slope Method= 2
Unsteady Bridges Friction Slope Method= 1
Parabolic Critical Depth
Global Vel Dist= 0 , 0 , 0
Global Log Level= 0
CheckData=True
Encroach Param=-1 ,0,0, 2
Encroach River=C102-00-00
Encroach Reach=C102-00-00_0008
Encroach Node=9683.9
       1  4940.4  5027.8
Encroach Node=9528.6
       1    4951  5035.7
Encroach Node=9517.0
       1    4951  5035.7
Encroach Node=7717.0
       1    4951  5035.7
Encroach Node=7569.0
       1  4972.8  5030.6
Encroach Node=7116.2
       1  4983.4 5043.62
Encroach Node=7073.9
       1    4980 5043.62
Encroach Node=6998.9
       1    4980 5043.62
Encroach Node=6896.5
       1 4984.26 5112.26
Encroach Node=6814.5
       1 4984.26 5112.26
Encroach Node=6714.3
       1  4980.8  5136.9
Encroach Node=6090.8
       1  4947.4  5136.9
Encroach Node=5374.9
       1    4925    5044
Encroach Node=5012.4
       1    4900    5050
Encroach Node=4966.4
       1    4900    5050
Encroach Node=4846.9
       1    4920    5050
Encroach Node=4840.4
       1  4964.6  5033.2
Encroach Node=4372.8
       1  4964.6  5033.2
Encroach Node=4318.2
       1    4915    5080
Encroach Node=4216.2
       1    4915    5080
Encroach Node=3967.5
       1    4952    5065
Encroach Node=3748.0
       1    4930    5045
Encroach Node=3682.7
       1  4972.8  5035.9
Encroach Node=3400.3
       1  4972.8  5035.9
Encroach Node=3330.6
       1    4910    5060
Encroach Node=3270.6
       1    4910    5060
Encroach Node=3152.4
       1    4875  5078.3
Encroach Node=3040.8
       1  4957.9  5078.3
Encroach Node=2936.2
       1  4957.9  5078.3
Encroach Node=2455.3
       1  4977.1  5054.4
Encroach Node=2172.3
       1    4960    5050
Encroach Node=2066.0
       1    4970    5080
Encroach Node=2039.8
       1    4970    5080
Encroach Node=2035.6
       1    4844 5070.12
Encroach Node=2007.2
       1    4844 5070.12
Encroach Node=1967.7
       1    4900    5045
Encroach Node=1945.7
       1    4900    5045
Encroach Node=1501.5
       1  4930.8  5044.2
Encroach Node=1146.1
       1  4977.9  5022.5
Encroach Node=1116.0
       1  4977.7  5022.5
Encroach Node=994.8
       1  4977.7  5022.5
Encroach Node=829.0
       1  4977.9  5032.8
BEGIN DESCRIPTION:
FEMA Effective Risk Map Study Floodway May 02, 2019
END DESCRIPTION:
Computation Interval=1HOUR
Output Interval=1HOUR
Run HTab= 0
Run UNet= 0
Run PostProcess= 0
Run WQNet= 0
UNET Theta= 1
UNET Theta Warmup= 1
UNET ZTol= 0.02
UNET ZSATol= 0.1
UNET MxIter= 20
UNET MaxInSteps= 20
UNET DtIC= 0
UNET DtMin= 0
UNET MaxCRTS= 20
UNET WFStab= 2
UNET SFStab= 1
UNET WFX= 1
UNET SFX= 1
UNET DSS MLevel= 4
UNET DZMax Abort= 100
UNET Convert EG Bridges=-1
UNET Use Existing IB Tables=-1
UNET Froude Reduction=False
UNET Froude Limit= 1
UNET Froude Power= 10
UNET Time Slicing=0,0, 5
UNET Junction Losses=0
Instantaneous Interval=1HOUR
DSS File=dss
Write IC File= 0
IC Time=0,,
Write IC File at Sim End=0
Echo Input=False
Echo Parameters=False
Echo Output=False
Write Detailed= 0
WQ AD Non Conservative
WQ ULTIMATE=-1
WQ Max Comp Step=1HOUR
WQ Output Interval=15MIN
WQ Output Selected Increments= 0
WQ Output face flow=0
WQ Output face velocity=0
WQ Output face area=0
WQ Output face dispersion=0
WQ Output cell volume=0
WQ Output cell surface area=0
WQ Output cell continuity=0
WQ Output cumulative cell continuity=0
WQ Output face conc=0
WQ Output face dconc_dx=0
WQ Output face courant=0
WQ Output face peclet=0
WQ Output face adv mass=0
WQ Output face disp mass=0
WQ Output cell mass=0
WQ Output cell source sink temp=0
WQ Output cell source sink nsm=0
WQ Output MaxMinRange=-1
WQ Daily Max Min Mean=-1
WQ Daily Range=0
WQ Daily Time=0
WQ Create Restart=0
WQ Fixed Restart=0
WQ System Summary=0
WQ Use Fixed Temperature=0
Sorting and Armoring Iterations= 10
XS Update Threshold= 0.02
Hydraulics Update Threshold= 0.02
Energy Slope Method= 1
Volume Change Method= 0
XS Weighting Method= 0
Number of US Weighted Cross Sections= 1
Number of DS Weighted Cross Sections= 1
Upstream XS Weight=0.25
Main XS Weight=0.5
Downstream XS Weight=0.25
Number of DS XS's Weighted with US Boundary= 1
Upstream Boundary Weight= 1
Weight of XSs Associated with US Boundary= 0
Number of US XS's Weighted with DS Boundary= 1
Downstream Boundary Weight= 0.5
Weight of XSs Associated with DS Boundary= 0.5
Sediment Output Level= 4
Mass or Volume Output= 0
Output Increment Type= 1
Profile and TS Output Increment= 10
XS Output Flag= 0
XS Output Increment= 10
Disregard all LS=0
Disregard all Conn=0
Disregard all Breaches=0
Disregard all Pumps=0

--- C102-00-00.p01 (plan) ---

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Plan Title=Effective Multi-Profile 2015
Short Identifier=Eff+Riskmap MP
Geom File=g01
Flow File=f01
Encroach Param=-1 ,0,0, 0
FEMA Effective Risk Map Study Multi-Profile May 02, 2019
UNET ZSATol= 0.05
UNET MaxInSteps= 0

--- C102-00-00.f02 (steady flow) ---

Flow Title=Effective Floodway 2015
Program Version=4.10
Number of Profiles= 2
Profile Names=1PCT_100yr,Floodway
River Rch & RM=C102-00-00,C102-00-00_0008 ,9683.9
    1221    1221
River Rch & RM=C102-00-00,C102-00-00_0008 ,6896.5
    1555    1555
River Rch & RM=C102-00-00,C102-00-00_0008 ,5012.4
    1830    1830
River Rch & RM=C102-00-00,C102-00-00_0008 ,4318.2
    1944    1944
River Rch & RM=C102-00-00,C102-00-00_0008 ,3682.7
    2054    2054
River Rch & RM=C102-00-00,C102-00-00_0008 ,3330.6
    2117    2117
River Rch & RM=C102-00-00,C102-00-00_0008 ,3040.8
    2171    2171
River Rch & RM=C102-00-00,C102-00-00_0008 ,2066
    2362    2362
River Rch & RM=C102-00-00,C102-00-00_0008 ,2021.4
    2371    2371
River Rch & RM=C102-00-00,C102-00-00_0008 ,1967.7
    2382    2382
River Rch & RM=C102-00-00,C102-00-00_0008 ,1116
    2565    2565
Boundary for River Rch & Prof#=C102-00-00,C102-00-00_0008 , 1
Up Type= 0
Dn Type= 3
Dn Slope=0.00072
Boundary for River Rch & Prof#=C102-00-00,C102-00-00_0008 , 2
Up Type= 0
Dn Type= 1
Dn Known WS=7.39
DSS Import GetInterval= 0
DSS Import GetPeak= 0
DSS Import FillOption= 0

--- C102-00-00.f01 (steady flow) ---

Flow Title=Effective Multi-Profile 2015
Program Version=4.10
Number of Profiles= 6
Profile Names=10PCT_10yr,4PCT_25yr,2PCT_50yr,1PCT_100yr,1PCT_Plus,0.2PCT_500yr
River Rch & RM=C102-00-00,C102-00-00_0008 ,9683.9
     672     856    1029    1221    1466    1796
River Rch & RM=C102-00-00,C102-00-00_0008 ,6896.5
     867    1102    1321    1555    1866    2247
River Rch & RM=C102-00-00,C102-00-00_0008 ,5012.4
    1030    1306    1563    1830    2196    2615
River Rch & RM=C102-00-00,C102-00-00_0008 ,4318.2
    1097    1390    1663    1944    2332    2765
River Rch & RM=C102-00-00,C102-00-00_0008 ,3682.7
    1163    1473    1761    2054    2464    2910
River Rch & RM=C102-00-00,C102-00-00_0008 ,3330.6
    1201    1520    1817    2117    2541    2994
River Rch & RM=C102-00-00,C102-00-00_0008 ,3040.8
    1233    1561    1865    2171    2605    3064
River Rch & RM=C102-00-00,C102-00-00_0008 ,2066
    1348    1704    2035    2362    2835    3314
River Rch & RM=C102-00-00,C102-00-00_0008 ,2021.4
    1354    1711    2043    2371    2846    3326
River Rch & RM=C102-00-00,C102-00-00_0008 ,1967.7
    1361    1719    2053    2382    2859    3340
River Rch & RM=C102-00-00,C102-00-00_0008 ,1116
    1471    1857    2215    2565    3078    3577
Boundary for River Rch & Prof#=C102-00-00,C102-00-00_0008 , 1
Up Type= 0
Dn Type= 3
Dn Slope=0.00072
Boundary for River Rch & Prof#=C102-00-00,C102-00-00_0008 , 2
Up Type= 0
Dn Type= 3
Dn Slope=0.00072
Boundary for River Rch & Prof#=C102-00-00,C102-00-00_0008 , 3
Up Type= 0
Dn Type= 3
Dn Slope=0.00072
Boundary for River Rch & Prof#=C102-00-00,C102-00-00_0008 , 4
Up Type= 0
Dn Type= 3
Dn Slope=0.00072
DSS Import GetInterval= 0
DSS Import GetPeak= 0
DSS Import FillOption= 0

--- C102-00-00.g01 (geometry) ---

Geom Title=C102-00-00 2015
Program Version=4.10

River Reach=C102-00-00      ,C102-00-00_0008
Reach XY= 30
      3148911.82     13821304.03      3149261.85      13821324.9
      3149458.57     13821476.52      3150164.81     13822201.23
       3150763.2     13822742.98      3150839.53     13823095.11
      3150903.56     13823245.33      3151080.86     13823481.72
      3151142.42      13823516.2      3151327.75       13823709.
      3151509.33       13823792.      3151519.18     13823897.88
      3151553.65     13823929.89      3151696.48     13823956.98
      3151873.78     13824092.42      3151947.65     13824198.31
      3152070.78     13824190.92      3152262.85     13824252.48
      3152851.25       13824768.      3153133.19     13824849.28
      3153384.32     13824837.33        3153505.       13824919.
        3153827.       13824933.      3154064.25       13824651.
      3154242.75       13824516.      3154505.28     13824405.61
      3154729.86     13824328.93      3154999.25       13824325.
      3155485.74     13824205.68        3155910.       13824162.

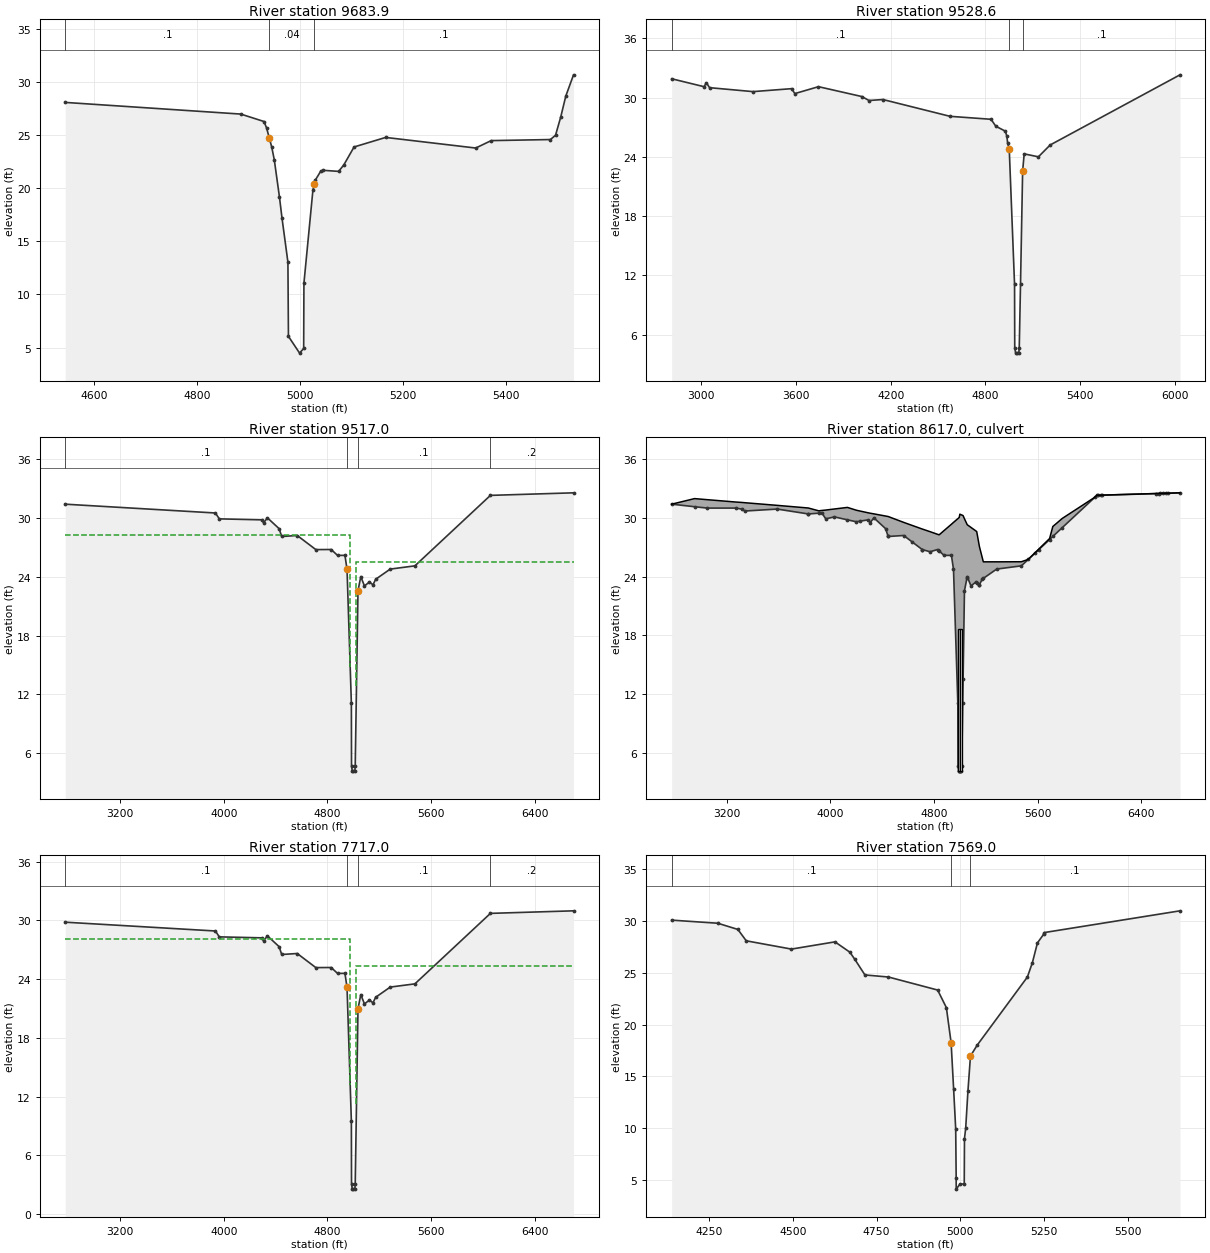
Type RM Length L Ch R = 1 ,9683.9  ,135.4,155.3,165.8
BEGIN DESCRIPTION:
Cross Section  9683.9
END DESCRIPTION:
XS GIS Cut Line= 5
      3148979.15     13821752.93      3148979.15      13821752.9
      3148974.96     13821446.67      3148874.28     13821146.73
       3148528.8     13821029.19
#Sta/Elev= 30
  4543.7    28.1  4884.9      27  4929.9    26.3  4934.9    25.7  4940.4   24.71
  4944.9    23.9  4949.9    22.7  4959.9    19.2  4964.9    17.2  4976.4   13.04
  4977.4    6.05  4999.1    4.47    5007    4.91  5007.5   11.06  5024.9    19.8
  5027.8   20.38  5029.9    20.8  5039.9    21.6  5044.9    21.7  5074.9    21.6
  5084.9    22.2  5104.9    23.9  5166.3    24.8  5341.3    23.8  5371.3    24.5
  5486.3    24.6  5496.3      25  5506.3    26.7  5516.3    28.7  5531.3    30.7
#Mann= 3 , 1 , 0
  4543.7      .1       0  4940.4     .04       0  5027.8      .1       0
Bank Sta=4940.4,5027.8
XS Rating Curve= 0 ,0
Exp/Cntr=0.3,0.1

Type RM Length L Ch R = 1 ,9528.6  ,13.3,11.6,11.3
BEGIN DESCRIPTION:
Cross Section 9528.6-Interpolated
END DESCRIPTION:
XS GIS Cut Line= 6
      3148417.15     13823351.84      3149000.31     13822234.52
      3149077.68     13821353.07      3149083.21     13821303.33
      3149094.26     13821098.86      3148437.47     13820608.08
#Sta/Elev= 30
  2812.6    31.9  3017.6    31.1  3032.6    31.5  3052.6      31  3327.6    30.6
  3572.6    30.9  3592.6    30.4  3742.6    31.1  4017.6    30.1  4062.6    29.7
  4150.6    29.8  4575.6    28.1  4835.6    27.8  4865.6    27.1  4925.6    26.6
  4935.6    26.1  4940.6    25.4    4951   24.75  4984.5   11.08  4985.7    4.69
    4991    4.16  5001.3    4.13  5011.6    4.17  5014.3    4.68  5022.3   11.11
  5035.7   22.55  5045.5    24.3  5135.5      24  5210.2    25.2  6032.5    32.3
#Mann= 3 , 1 , 0
  2812.6      .1       0    4951     .04       0  5035.7      .1       0
Bank Sta=4951,5035.7
XS Rating Curve= 0 ,0
Exp/Cntr=0.5,0.3

Type RM Length L Ch R = 1 ,9517.0  ,1800,1800,1800
BEGIN DESCRIPTION:
Upstream Section of Bridge/Culvert/Weir
END DESCRIPTION:
XS GIS Cut Line= 6
      3147769.69     13822861.31      3148436.43     13821887.11
      3148522.07     13821746.43      3149218.09     13821165.87
      3149433.43     13820804.49       3149883.7     13819634.81
#Sta/Elev= 30
  2774.6   31.42  3934.6   30.52  3964.6   29.92  4291.5   29.82  4306.5   29.52
  4336.5   30.02  4426.5   28.92  4446.5   28.12  4566.5   28.22  4710.1   26.78
  4828.4   26.79  4877.7   26.19  4934.9   26.19    4951   24.77  4984.5    11.1
  4985.7    4.71    4991    4.18  5000.2    4.15  5011.6    4.19  5014.3     4.7
  5035.7   22.57  5057.2   24.02  5085.7   23.07  5124.4   23.47  5151.2   23.18
  5172.3   23.75  5284.6   24.79  5475.2   25.12  6058.4   32.32  6700.2   32.58
#Mann= 4 , 1 , 0
  2774.6      .1       0    4951     .04       0  5035.7      .1       0
  6058.4      .2       0
#XS Ineff= 2 , 0
       0  4975.4    28.3    5024       0    25.5
Permanent Ineff=
       F       F
Bank Sta=4951,5035.7
XS Rating Curve= 0 ,0
Exp/Cntr=0.5,0.3

Type RM Length L Ch R = 2 ,8617.0  ,,,
BEGIN DESCRIPTION:
FENNEL ROAD
Structure ID: C02-15
END DESCRIPTION:
Bridge Culvert--1,0,-1,-1, 0
Deck Dist Width WeirC Skew NumUp NumDn MinLoCord MaxHiCord MaxSubmerge Is_Ogee
10,1780,3,0, 53, 53, , , 0.95, 0, 1,1,,
  2774.6  2951.1  3049.6  3269.6  3314.6  3339.6  3589.6  3829.6  3911.1  3934.6
  3964.6  4031.5  4131.9  4201.5  4291.5  4306.5  4336.5  4426.5  4446.5  4566.5
  4710.1  4770.5  4828.4  4840.2  4877.7  4934.9    4951  4984.5  4985.7    4991
  4995.2  5000.2  5011.6  5014.3  5022.3  5025.2  5035.7  5057.2  5085.7  5124.4
  5130.2  5151.2  5172.3  5181.5  5284.6  5475.2  5528.1  5693.1  5718.1  5791.6
  6041.6  6058.4  6700.2
    31.4   31.97   31.86   31.62   31.58   31.55   31.28   31.01   30.72   30.76
    30.8   30.91   31.07   30.78   30.52   30.48   30.41   30.19   30.14   29.54
   28.86   28.59   28.32   28.27    28.7   29.35   29.54   29.92   29.93   29.99
   30.04   30.38   30.31    30.3   30.25   30.23   29.91    29.3   29.03   28.66
   28.61   27.07   25.98   25.51   25.51   25.52   25.76   27.89   29.12   29.95
    32.1   32.31   32.56
    31.4   31.14      31      31    30.9    30.7    30.9    30.4   30.48    30.5
    29.9    30.1    29.8    29.6    29.8    29.5      30    28.9    28.1    28.2
   26.76   26.54   26.77   26.63   26.17   26.17   24.75   11.08    4.69    4.16
    4.15    4.13    4.17    4.68   11.11   13.59   22.55      24   23.05   23.45
   23.39   23.16   23.73   23.82   24.77    25.1   25.75   27.79    28.1   29.01
   32.09    32.3   32.56
  2774.6  2951.1  3049.6  3269.6  3314.6  3339.6  3589.6  3829.6  3911.1  3934.6
  3964.6  4031.5  4131.9  4201.5  4291.5  4306.5  4336.5  4426.5  4446.5  4566.5
  4710.1  4770.5  4828.4  4840.2  4877.7  4934.9    4951  4984.5  4985.7    4991
  4995.2  5000.2  5011.6  5014.3  5022.3  5025.2  5035.7  5057.2  5085.7  5124.4
  5130.2  5151.2  5172.3  5181.5  5284.6  5475.2  5528.1  5693.1  5718.1  5791.6
  6041.6  6058.4  6700.2
    31.4   31.97   31.86   31.62   31.58   31.55   31.28   31.01   30.72   30.76
    30.8   30.91   31.07   30.78   30.52   30.48   30.41   30.19   30.14   29.54
   28.86   28.59   28.32   28.27    28.7   29.35   29.54   29.92   29.93   29.99
   30.04   30.38   30.31    30.3   30.25   30.23   29.91    29.3   29.03   28.66
   28.61   27.07   25.98   25.51   25.51   25.52   25.76   27.89   29.12   29.95
    32.1   32.31   32.56
   29.72   29.46   29.32   29.32   29.22   29.02   29.22   28.72    28.8   28.82
   28.22   28.42   28.12   27.92   28.12   27.82   28.32   27.22   26.42   26.52
   25.08   24.86   25.09   24.95   24.49   24.49   23.07     9.4    3.01    2.48
    2.47    2.45    2.49       3    9.43   11.91   20.87   22.32   21.37   21.77
   21.71   21.48   22.05   22.14   23.09   23.42   24.07   26.11   26.42   27.33
   30.41   30.62   30.88
BR Coef= 1 , 0 , 0 ,1.25, 0 ,,,0.8,-1,2,0,
WSPro=,,,, 1 ,,,, 0 ,,,, 0 ,,,,-1 ,-1 ,-1 , 0 , 0 , 0 , 0 , 0
Culvert=2,14.5,14,1780,0.015,0.4,1,8,1,4.15,4992.4,2.34,4992.4,Culvert #1  , 0 ,10
Culvert Bottom n=0.015
Culvert=2,14.5,14,1780,0.015,0.4,1,8,1,4.15,5007,2.34,5007,Culvert #2  , 0 ,10
Culvert Bottom n=0.015
BR U #Sta/Elev= 72
  2774.6    31.4  2951.1   31.14  3049.6      31  3269.6      31  3314.6    30.9
  3339.6    30.7  3589.6    30.9  3826.1   30.41  3829.6    30.4  3911.1   30.48
  3934.6    30.5  3964.6    29.9  4031.5    30.1  4131.9    29.8  4201.5    29.6
  4226.9   29.66  4291.5    29.8  4306.5    29.5  4336.5      30  4426.5    28.9
  4445.2   28.15  4446.5    28.1  4566.5    28.2  4630.2   27.56  4710.1   26.76
  4710.2   26.76  4770.5   26.54  4828.4   26.77  4840.2   26.63  4877.7   26.17
  4934.9   26.17    4951   24.75  4984.5   11.08  4985.7    4.69    4991    4.16
  4995.2    4.15  5000.2    4.13  5001.3    4.13  5011.6    4.17  5014.3    4.68
  5022.3   11.11  5025.2   13.59  5035.7   22.55  5055.2   23.87  5057.2      24
  5085.7   23.05  5124.4   23.45  5130.2   23.39  5151.2   23.16  5151.5   23.17
  5172.3   23.73  5181.5   23.82  5284.6   24.77  5475.2    25.1  5528.1   25.75
  5578.1   26.37  5608.1   26.74  5693.1   27.79  5718.1    28.1  5791.6   29.01
  6041.6   32.09  6058.4    32.3  6066.6    32.3  6091.6   32.31  6101.6   32.32
  6511.6   32.48  6536.6   32.49  6546.6    32.5  6566.6   32.51  6591.6   32.52
  6606.6   32.52  6700.2   32.56
BR U #Mann= 4
  2774.6      .1    4951     .04  5035.7      .1  6058.4      .2
BR U Banks=4951,5035.7
BR D #Sta/Elev= 72
  2774.6   29.72  2951.1   29.46  3049.6   29.32  3269.6   29.32  3314.6   29.22
  3339.6   29.02  3589.6   29.22  3826.1   28.73  3829.6   28.72  3911.1    28.8
  3934.6   28.82  3964.6   28.22  4031.5   28.42  4131.9   28.12  4201.5   27.92
  4226.9   27.98  4291.5   28.12  4306.5   27.82  4336.5   28.32  4426.5   27.22
  4445.2   26.47  4446.5   26.42  4566.5   26.52  4630.2   25.88  4710.1   25.08
  4710.2   25.08  4770.5   24.86  4828.4   25.09  4840.2   24.95  4877.7   24.49
  4934.9   24.49    4951   23.07  4984.5     9.4  4985.7    3.01    4991    2.48
  4995.2    2.47  5000.2    2.45  5001.3    2.45  5011.6    2.49  5014.3       3
  5022.3    9.43  5025.2   11.91  5035.7   20.87  5055.2   22.19  5057.2   22.32
  5085.7   21.37  5124.4   21.77  5130.2   21.71  5151.2   21.48  5151.5   21.49
  5172.3   22.05  5181.5   22.14  5284.6   23.09  5475.2   23.42  5528.1   24.07
  5578.1   24.69  5608.1   25.06  5693.1   26.11  5718.1   26.42  5791.6   27.33
  6041.6   30.41  6058.4   30.62  6066.6   30.62  6091.6   30.63  6101.6   30.64
  6511.6    30.8  6536.6   30.81  6546.6   30.82  6566.6   30.83  6591.6   30.84
  6606.6   30.84  6700.2   30.88
BR D #Mann= 4
  2774.6      .1    4951     .04  5035.7      .1  6058.4      .2
BR D Banks=4951,5035.7
BC Design=,, 0 ,, 0 ,,,,,,
BC HTab HWMax=32.58
BC Use User HTab Curves=0
BC User HTab FreeFlow(D)= 0

Type RM Length L Ch R = 1 ,7717.0  ,148,148,148
BEGIN DESCRIPTION:
Downstream Section of Bridge/Culvert/Weir
END DESCRIPTION:
XS GIS Cut Line= 6
      3149006.61     13824168.99      3149673.35     13823194.79
      3149758.99     13823054.11      3150455.01     13822473.55
      3150670.35     13822112.17      3151120.62     13820942.49
#Sta/Elev= 30
  2774.6   29.82  3934.6   28.92  3964.6   28.32  4291.5   28.22  4306.5   27.92
  4336.5   28.42  4426.5   27.32  4446.5   26.52  4566.5   26.62  4710.1   25.18
  4828.4   25.19  4877.7   24.59  4934.9   24.59    4951   23.17  4984.5     9.5
  4985.7    3.11    4991    2.58  5000.2    2.55  5011.6    2.59  5014.3     3.1
  5035.7   20.97  5057.2   22.42  5085.7   21.47  5124.4   21.87  5151.2   21.58
  5172.3   22.15  5284.6   23.19  5475.2   23.52  6058.4   30.72  6700.2   30.98
#Mann= 4 , 1 , 0
  2774.6      .1       0    4951     .04       0  5035.7      .1       0
  6058.4      .2       0
#XS Ineff= 2 , 0
       0  4975.4    28.1    5024       0    25.3
Permanent Ineff=
       F       F
Bank Sta=4951,5035.7
XS Rating Curve= 0 ,0
Exp/Cntr=0.5,0.3

Type RM Length L Ch R = 1 ,7569.0  ,452.7,452.8,480.6
BEGIN DESCRIPTION:
Cross Section 7569.0
END DESCRIPTION:
XS GIS Cut Line= 6
      3149868.43     13823054.82      3150040.47      13822996.7
       3150350.9     13822753.39      3150447.38     13822690.46
      3150720.05     13822312.92      3151042.44      13822150.3
#Sta/Elev= 30
  4138.3    30.1    4276    29.8    4336    29.2    4361    28.1    4496    27.3
    4626      28  4670.4      27  4685.4    26.3  4715.4    24.8  4785.6    24.6
  4932.6   23.34  4958.6   21.64  4972.8   18.25  4980.3   13.76  4986.5     9.9
  4987.9    5.13    4988    4.09  4999.4    4.59    5012    4.58  5012.7    8.98
  5016.3    9.97    5023   13.56  5030.6   16.96  5050.4      18  5200.6    24.6
  5215.6      26  5230.6    27.9  5250.6    28.8  5251.3    28.9  5656.3      31
#Mann= 3 , 1 , 0
  4138.3      .1       0  4972.8     .04       0  5030.6      .1       0
Bank Sta=4972.8,5030.6
XS Rating Curve= 0 ,0
Exp/Cntr=0.3,0.1

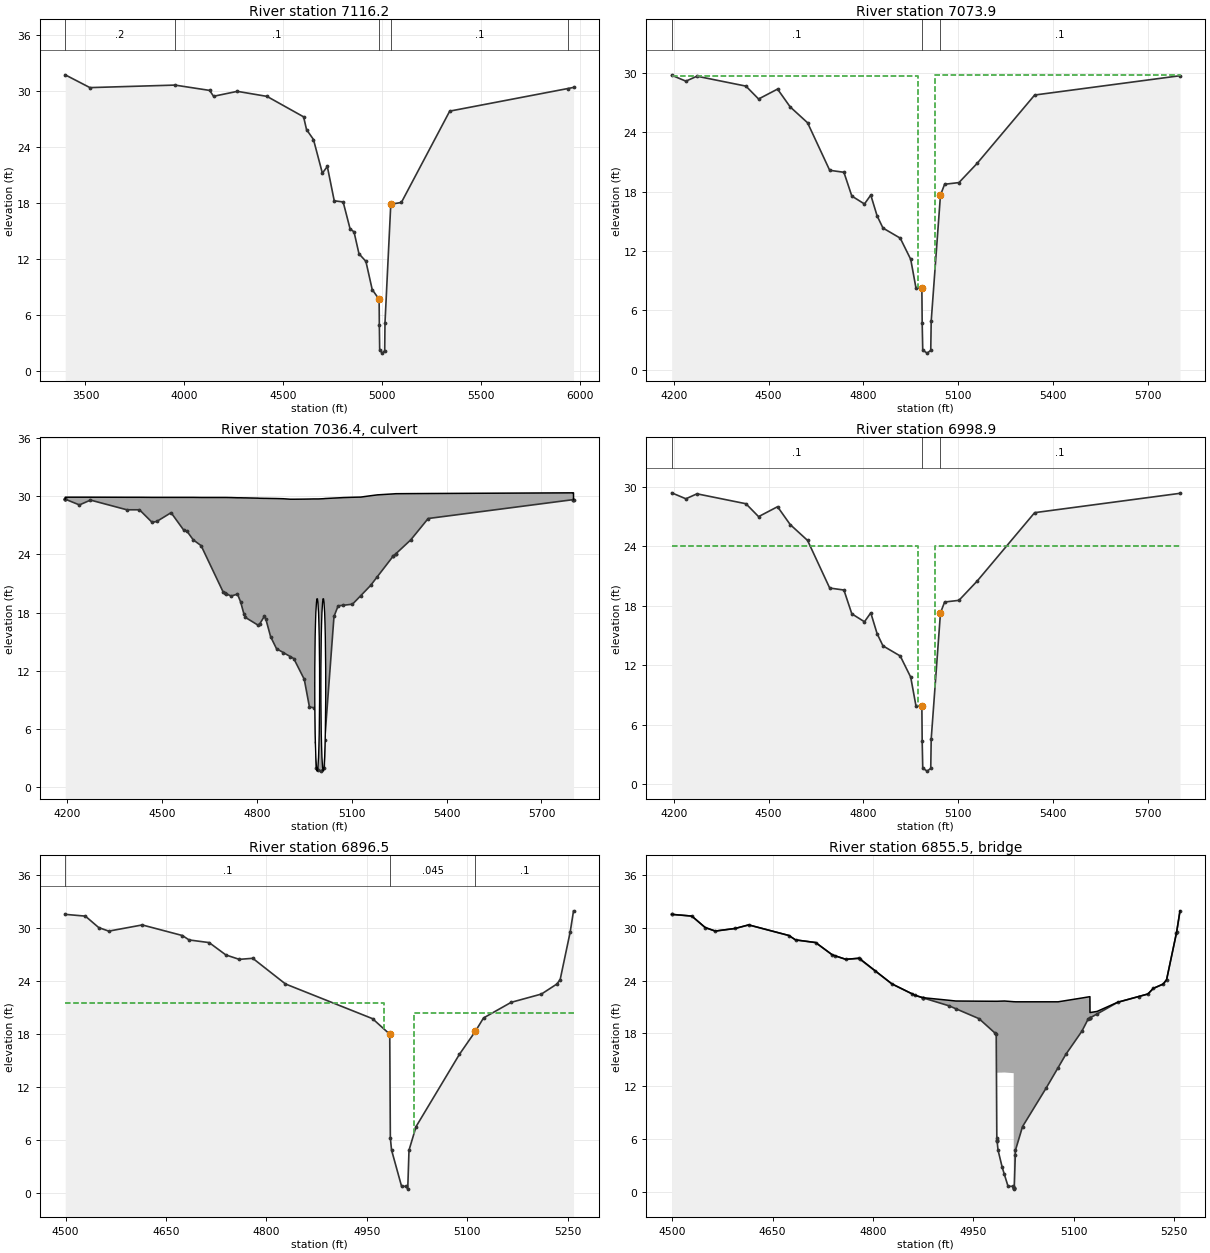
Type RM Length L Ch R = 1 ,7116.2  ,40.3,42.3,45.9
BEGIN DESCRIPTION:
Cross Section 7116.2-Interpolated
END DESCRIPTION:
XS GIS Cut Line= 5
      3149754.84      13824140.1      3150762.79     13822953.55
      3150813.69     13822895.24      3150897.45     13822796.64
      3151427.21     13822189.26
#Sta/Elev= 30
  3397.8   31.71  3522.8   30.34  3952.8   30.61  4127.8   30.04  4147.8   29.41
  4267.8   29.94  4417.8    29.4  4602.8   27.21  4617.8   25.84  4652.8   24.78
  4697.8   21.17  4722.8   21.89  4757.8   18.21  4802.8   18.09  4837.8   15.21
  4857.8   14.88  4882.8   12.54  4917.8   11.72  4949.7     8.7  4984.7    7.65
 4985.73    4.93 4987.54    2.19 5001.56    1.89 5012.87    2.17 5014.27    5.12
 5043.62   17.85  5097.1   18.03  5341.5   27.82  5938.2   30.24  5967.4   30.36
#Mann= 5 , 1 , 0
  3397.8      .2       0  3952.8      .1       0  4984.7    .045       0
 5043.62      .1       0  5938.2      .2       0
Bank Sta=4984.7,5043.62
XS Rating Curve= 0 ,0
Exp/Cntr=0.5,0.3

Type RM Length L Ch R = 1 ,7073.9  ,75,75,75
BEGIN DESCRIPTION:
Upstream Section of Bridge/Culvert/Weir
END DESCRIPTION:
XS GIS Cut Line= 3
       3150270.8     13823564.61      3150861.41     13822889.15
      3151334.51     13822358.19
#Sta/Elev= 30
  4193.1   29.75  4238.1   29.15  4273.1   29.65  4428.1   28.65  4468.1   27.35
  4528.1   28.35  4568.1   26.55  4623.1   24.95  4693.1   20.15  4738.1   19.95
  4763.1   17.55  4803.1   16.75  4823.1   17.65  4843.1   15.55 4861.67   14.32
 4916.28    13.3 4949.49   11.16 4965.89     8.3 4984.75    8.24 4985.73    4.73
 4987.54    1.99 5001.56    1.69 5012.87    1.97 5014.27    4.92 5043.62   17.65
 5056.74   18.74 5102.09   18.91 5159.33   20.84  5341.6   27.75 5801.51    29.7
#Mann= 3 , 1 , 0
  4193.1      .1       0 4984.75    .045       0 5043.62      .1       0
#XS Ineff= 2 , 0
       0    4973    29.7  5026.2       0   29.79
Permanent Ineff=
       F       F
Bank Sta=4984.75,5043.62
XS Rating Curve= 0 ,0
Exp/Cntr=0.5,0.3

Type RM Length L Ch R = 2 ,7036.4  ,,,
BEGIN DESCRIPTION:
SOUTHERN PACIFIC RAILROAD, SKEW ANGLE OF 35 DEGREES
Structure ID: C02-14
END DESCRIPTION:
Bridge Culvert--1,0,-1,-1, 0
Deck Dist Width WeirC Skew NumUp NumDn MinLoCord MaxHiCord MaxSubmerge Is_Ogee
10,55,2.6,0, 58, 58, , , 0.95, 0, 1,1,,
  4193.1 4193.29  4193.4 4193.51  4238.1  4273.1  4388.1  4428.1  4468.1  4483.1
  4528.1  4568.1  4578.1  4598.1  4623.1  4693.1  4699.6  4702.2  4718.1  4738.1
  4748.1  4758.1  4763.1  4803.1  4808.1  4823.1  4828.1  4843.1 4861.67  4883.7
  4905.1 4916.28 4949.49 4965.89 4979.83 4984.75 4985.73 4987.54  4994.3 5001.56
 5012.87 5014.27 5043.62 5056.74  5073.3 5102.09  5128.3 5159.33    5181  5231.4
 5231.57    5239  5239.6  5286.6  5341.6 5801.29  5801.4 5801.51
    29.7   29.71    29.9    29.9    29.9    29.9   29.89   29.89   29.88   29.88
   29.88   29.88   29.88   29.88   29.87   29.87   29.87   29.87   29.86   29.84
   29.84   29.83   29.83    29.8   29.79   29.78   29.78   29.77   29.76   29.74
   29.69   29.69    29.7   29.71   29.72   29.72   29.72   29.72   29.72   29.73
   29.75   29.76   29.81   29.83   29.86   29.89   29.91   30.05   30.14   30.24
   30.24   30.26   30.26   30.27   30.28   30.35   30.35   29.65
    29.7    29.7    29.7   29.69    29.1    29.6    28.6    28.6    27.3    27.4
    28.3    26.5    26.4    25.5    24.9    20.1      20   19.95    19.7    19.9
    19.1    17.9    17.5    16.7    16.8    17.6    17.3    15.5   14.27   13.86
   13.46   13.25   11.11    8.25    8.18    8.19    4.68    1.94     1.8    1.64
    1.92    4.87    17.6   18.69   18.75   18.86   19.74   20.79   21.71   23.84
   23.82   24.05   24.07    25.5    27.7   29.65   29.65   29.65
  4193.1 4193.29  4193.4 4193.51  4238.1  4273.1  4388.1  4428.1  4468.1  4483.1
  4528.1  4568.1  4578.1  4598.1  4623.1  4693.1  4699.6  4702.2  4718.1  4738.1
  4748.1  4758.1  4763.1  4803.1  4808.1  4823.1  4828.1  4843.1 4861.67  4883.7
  4905.1 4916.28 4949.49 4965.89 4979.83 4984.75 4985.73 4987.54  4994.3 5001.56
 5012.87 5014.27 5043.62 5056.74  5073.3 5102.09  5128.3 5159.33    5181  5231.4
 5231.57    5239  5239.6  5286.6  5341.6 5801.29  5801.4 5801.51
    29.7   29.71    29.9    29.9    29.9    29.9   29.89   29.89   29.88   29.88
   29.88   29.88   29.88   29.88   29.87   29.87   29.87   29.87   29.86   29.84
   29.84   29.83   29.83    29.8   29.79   29.78   29.78   29.77   29.76   29.74
   29.69   29.69    29.7   29.71   29.72   29.72   29.72   29.72   29.72   29.73
   29.75   29.76   29.81   29.83   29.86   29.89   29.91   30.05   30.14   30.24
   30.24   30.26   30.26   30.27   30.28   30.35   30.35   29.65
   29.45   29.45   29.45   29.44   28.85   29.35   28.35   28.35   27.05   27.15
   28.05   26.25   26.15   25.25   24.65   19.85   19.75    19.7   19.45   19.65
   18.85   17.65   17.25   16.45   16.55   17.35   17.05   15.25   14.02   13.61
   13.21      13   10.86       8    7.93    7.94    4.43    1.69    1.55    1.39
    1.67    4.62   17.35   18.44    18.5   18.61   19.49   20.54   21.46   23.59
   23.57    23.8   23.82   25.25   27.45    29.4    29.4    29.4
BR Coef= 1 , 0 , 0 ,1.25, 0 ,,,0.8,-1,2,0,
WSPro=,,,, 1 ,,,, 0 ,,,, 0 ,,,,-1 ,-1 ,-1 , 0 , 0 , 0 , 0 , 0
Culvert=5,17.8,15.3,55,0.025,0.4,1,41,1,1.64,4990.4,1.39,4990.4,Culvert #1  , 0 ,10
Culvert Bottom n=0.025
Culvert=5,17.8,15.3,55,0.025,0.4,1,41,1,1.64,5009.7,1.39,5009.7,Culvert #2  , 0 ,10
Culvert Bottom n=0.025
BR U #Sta/Elev= 58
  4193.1    29.7 4193.29    29.7  4193.4    29.7 4193.51   29.69  4238.1    29.1
  4273.1    29.6  4388.1    28.6  4428.1    28.6  4468.1    27.3  4483.1    27.4
  4528.1    28.3  4568.1    26.5  4578.1    26.4  4598.1    25.5  4623.1    24.9
  4693.1    20.1  4699.6      20  4702.2   19.95  4718.1    19.7  4738.1    19.9
  4748.1    19.1  4758.1    17.9  4763.1    17.5  4803.1    16.7  4808.1    16.8
  4823.1    17.6  4828.1    17.3  4843.1    15.5 4861.67   14.27  4883.7   13.86
  4905.1   13.46 4916.28   13.25 4949.49   11.11 4965.89    8.25 4979.83    8.18
 4984.75    8.19 4985.73    4.68 4987.54    1.94  4994.3     1.8 5001.56    1.64
 5012.87    1.92 5014.27    4.87 5043.62    17.6 5056.74   18.69  5073.3   18.75
 5102.09   18.86  5128.3   19.74 5159.33   20.79    5181   21.71  5231.4   23.84
 5231.57   23.82    5239   24.05  5239.6   24.07  5286.6    25.5  5341.6    27.7
 5801.29   29.65  5801.4   29.65 5801.51   29.65
BR U #Mann= 3
  4193.1      .1 4984.75    .045 5043.62      .1
BR U Banks=4984.75,5043.62
BR D #Sta/Elev= 58
  4193.1   29.45 4193.29   29.45  4193.4   29.45 4193.51   29.44  4238.1   28.85
  4273.1   29.35  4388.1   28.35  4428.1   28.35  4468.1   27.05  4483.1   27.15
  4528.1   28.05  4568.1   26.25  4578.1   26.15  4598.1   25.25  4623.1   24.65
  4693.1   19.85  4699.6   19.75  4702.2    19.7  4718.1   19.45  4738.1   19.65
  4748.1   18.85  4758.1   17.65  4763.1   17.25  4803.1   16.45  4808.1   16.55
  4823.1   17.35  4828.1   17.05  4843.1   15.25 4861.67   14.02  4883.7   13.61
  4905.1   13.21 4916.28      13 4949.49   10.86 4965.89       8 4979.83    7.93
 4984.75    7.94 4985.73    4.43 4987.54    1.69  4994.3    1.55 5001.56    1.39
 5012.87    1.67 5014.27    4.62 5043.62   17.35 5056.74   18.44  5073.3    18.5
 5102.09   18.61  5128.3   19.49 5159.33   20.54    5181   21.46  5231.4   23.59
 5231.57   23.57    5239    23.8  5239.6   23.82  5286.6   25.25  5341.6   27.45
 5801.29    29.4  5801.4    29.4 5801.51    29.4
BR D #Mann= 3
  4193.1      .1 4984.75    .045 5043.62      .1
BR D Banks=4984.75,5043.62
BC Design=,, 0 ,, 0 ,,,,,,
BC HTab HWMax=29.75
BC Use User HTab Curves=0
BC User HTab FreeFlow(D)= 0

Type RM Length L Ch R = 1 ,6998.9  ,102.4,102.4,102.4
BEGIN DESCRIPTION:
Downstream Section of Bridge/Culvert/Weir
END DESCRIPTION:
XS GIS Cut Line= 3
      3150290.12     13823637.08      3150880.73     13822961.61
      3151353.83     13822430.66
#Sta/Elev= 30
  4193.1   29.37  4238.1   28.77  4273.1   29.27  4428.1   28.27  4468.1   26.97
  4528.1   27.97  4568.1   26.17  4623.1   24.57  4693.1   19.77  4738.1   19.57
  4763.1   17.17  4803.1   16.37  4823.1   17.27  4843.1   15.17 4861.67   13.94
 4916.28   12.92 4949.49   10.78 4965.89    7.92 4984.75    7.86 4985.73    4.35
 4987.54    1.61 5001.56    1.31 5012.87    1.59 5014.27    4.54 5043.62   17.27
 5056.74   18.36 5102.09   18.53 5159.33   20.46  5341.6   27.37 5801.51   29.32
#Mann= 3 , 1 , 0
  4193.1      .1       0 4984.75    .045       0 5043.62      .1       0
#XS Ineff= 2 , 0
       0    4973      24  5026.2       0      24
Permanent Ineff=
       F       F
Bank Sta=4984.75,5043.62
XS Rating Curve= 0 ,0
Exp/Cntr=0.5,0.3

Type RM Length L Ch R = 1 ,6896.5  ,82,82,82
BEGIN DESCRIPTION:
Upstream Section of Bridge/Culvert/Weir
END DESCRIPTION:
XS GIS Cut Line= 3
      3150512.24     13823476.09      3150827.57     13823117.66
      3151010.95     13822903.16
#Sta/Elev= 30
  4499.3   31.59  4529.4   31.39  4549.4   30.09  4564.4   29.69  4614.4   30.39
  4674.4   29.19  4684.4   28.69  4714.4   28.39  4739.4   26.99  4759.4   26.49
 4779.58   26.61 4828.46    23.7 4958.51   19.77 4984.26   18.01 4985.16    6.24
 4986.96    4.88 5001.97     .76  5009.1     .77 5011.15     .45 5013.04    4.86
 5023.62    7.54  5088.4   15.73 5112.26   18.34 5124.41   19.85 5165.72   21.62
 5210.99   22.56  5233.9   23.69  5238.9   24.19  5253.9   29.59  5258.9   31.99
#Mann= 3 , 1 , 0
  4499.3      .1       0 4984.26    .045       0 5112.26      .1       0
#XS Ineff= 2 , 0
       0  4975.5   21.55  5020.4       0   20.38
Permanent Ineff=
       F       F
Bank Sta=4984.26,5112.26
XS Rating Curve= 0 ,0
Exp/Cntr=0.5,0.3

Type RM Length L Ch R = 3 ,6855.5  ,,,
BEGIN DESCRIPTION:
GALVESTON ROAD, SKEW ANGLE OF 35 DEGREES
Structure ID: C02-13
END DESCRIPTION:
Bridge Culvert--1,0,-1,-1, 0
Deck Dist Width WeirC Skew NumUp NumDn MinLoCord MaxHiCord MaxSubmerge Is_Ogee
10,62,2.6,0, 43, 43, , , 0.95, 0, 1,1,,
  4499.3  4529.4  4549.4  4564.4  4594.4  4614.4  4674.4  4684.4  4714.4  4739.4
  4759.4 4779.58 4828.46 4863.31 4874.49  4913.9  4923.7 4958.51 4984.26 4985.16
 4985.48 4985.57  4996.5 5010.39  5010.5 5011.15 5013.04 5023.62 5059.04  5076.8
  5088.4 5112.26 5121.69  5124.3 5124.41    5135 5165.72 5210.99  5218.9  5233.9
  5238.9  5253.9  5258.9
    31.5   31.31   30.01   29.61   29.91   30.31   29.11   28.61   28.31   26.91
   26.41   26.53   23.62   22.32   22.06   21.76   21.68   21.66   21.65   21.65
   21.65   21.65   21.68    21.6    21.6    21.6   21.59   21.59   21.59   21.59
   21.73   22.02   22.14   22.17   20.37    20.5   21.54   22.48   23.11   23.61
   24.11    29.5    31.9
    31.5    31.3      30    29.6    29.9    30.3    29.1    28.6    28.3    26.9
    26.4   26.52   23.61   22.31   22.05   21.13   20.81   19.68   17.92    6.15
    5.91   13.55   13.58    13.5     .46     .36    4.77    7.45   11.83   14.13
   15.64   18.25   19.64   19.75   19.76   20.21   21.53   22.47    23.1    23.6
    24.1    29.5    31.9
  4499.3  4529.4  4549.4  4564.4  4594.4  4614.4  4674.4  4684.4  4714.4  4739.4
  4759.4 4779.58 4828.46 4863.31 4874.49  4913.9  4923.7 4958.51 4984.26 4985.16
 4985.48 4985.57  4996.5 5010.39  5010.5 5011.15 5013.04 5023.62 5059.04  5076.8
  5088.4 5112.26 5121.69  5124.3 5124.41    5135 5165.72 5210.99  5218.9  5233.9
  5238.9  5253.9  5258.9
    31.5   31.31   30.01   29.61   29.91   30.31   29.11   28.61   28.31   26.91
   26.41   26.53   23.62   22.32   22.06   21.76   21.68   21.66   21.65   21.65
   21.65   21.65   21.68    21.6    21.6    21.6   21.59   21.59   21.59   21.59
   21.73   22.02   22.14   22.17   20.37    20.5   21.54   22.48   23.11   23.61
   24.11    29.5    31.9
   31.34   31.14   29.84   29.44   29.74   30.14   28.94   28.44   28.14   26.74
   26.24   26.36   23.45   22.15   21.89   20.97   20.65   19.52   17.76    5.99
    5.75   13.39   13.42   13.34      .3      .2    4.61    7.29   11.67   13.97
   15.48   18.09   19.48   19.59    19.6   20.05   21.37   22.31   22.94   23.44
   23.94   29.34   31.74
BR Coef= 1 , 1 , 0 ,1.25, 0 ,,,0.8,0,2,0,
WSPro=,,,, 1 ,,,, 0 ,,,, 0 ,,,,-1 ,-1 ,-1 , 0 , 0 , 0 , 0 , 0
BR U #Sta/Elev= 61
  4499.3    31.5  4499.4    31.5  4529.4    31.3  4549.4      30  4564.4    29.6
  4594.4    29.9  4614.4    30.3  4674.4    29.1  4684.4    28.6  4714.4    28.3
  4739.4    26.9    4743   26.81  4759.4    26.4 4779.58   26.52  4780.4   26.43
  4803.7   25.06 4828.46   23.61  4858.4   22.49 4863.31   22.31 4874.49   22.05
  4874.6   22.05 4874.71   22.04  4913.9   21.13  4923.7   20.81 4958.51   19.68
  4982.4   18.05 4984.26   17.92 4985.16    6.15 4985.48    5.91 4985.57    5.84
 4985.65    5.78 4986.96    4.79 4993.19    2.84  4996.5    2.02 5001.97     .67
  5009.1     .68 5010.31     .49 5010.39     .48  5010.5     .46 5011.15     .36
  5012.8    4.21 5013.04    4.77 5023.62    7.45 5059.04   11.83  5076.8   14.13
  5088.4   15.64 5112.26   18.25 5121.69   19.64 5124.19   19.75  5124.3   19.75
 5124.41   19.76    5135   20.21 5165.72   21.53  5197.1   22.18 5210.99   22.47
  5218.9    23.1  5233.9    23.6  5238.9    24.1  5253.6   29.39  5253.9    29.5
  5258.9    31.9
BR U #Mann= 3
  4499.3      .1 4984.26    .045 5112.26      .1
BR U Banks=4984.26,5112.26
BR D #Sta/Elev= 61
  4499.3   31.34  4499.4   31.34  4529.4   31.14  4549.4   29.84  4564.4   29.44
  4594.4   29.74  4614.4   30.14  4674.4   28.94  4684.4   28.44  4714.4   28.14
  4739.4   26.74    4743   26.65  4759.4   26.24 4779.58   26.36  4780.4   26.27
  4803.7    24.9 4828.46   23.45  4858.4   22.33 4863.31   22.15 4874.49   21.89
  4874.6   21.89 4874.71   21.88  4913.9   20.97  4923.7   20.65 4958.51   19.52
  4982.4   17.89 4984.26   17.76 4985.16    5.99 4985.48    5.75 4985.57    5.68
 4985.65    5.62 4986.96    4.63 4993.19    2.68  4996.5    1.86 5001.97     .51
  5009.1     .52 5010.31     .33 5010.39     .32  5010.5      .3 5011.15      .2
  5012.8    4.05 5013.04    4.61 5023.62    7.29 5059.04   11.67  5076.8   13.97
  5088.4   15.48 5112.26   18.09 5121.69   19.48 5124.19   19.59  5124.3   19.59
 5124.41    19.6    5135   20.05 5165.72   21.37  5197.1   22.02 5210.99   22.31
  5218.9   22.94  5233.9   23.44  5238.9   23.94  5253.6   29.23  5253.9   29.34
  5258.9   31.74
BR D #Mann= 3
  4499.3      .1 4984.26    .045 5112.26      .1
BR D Banks=4984.26,5112.26
BC Design=,, 0 ,, 0 ,,,,,,
BC HTab HWMax=31.99
BC Use User HTab Curves=0
BC User HTab FreeFlow(D)= 0