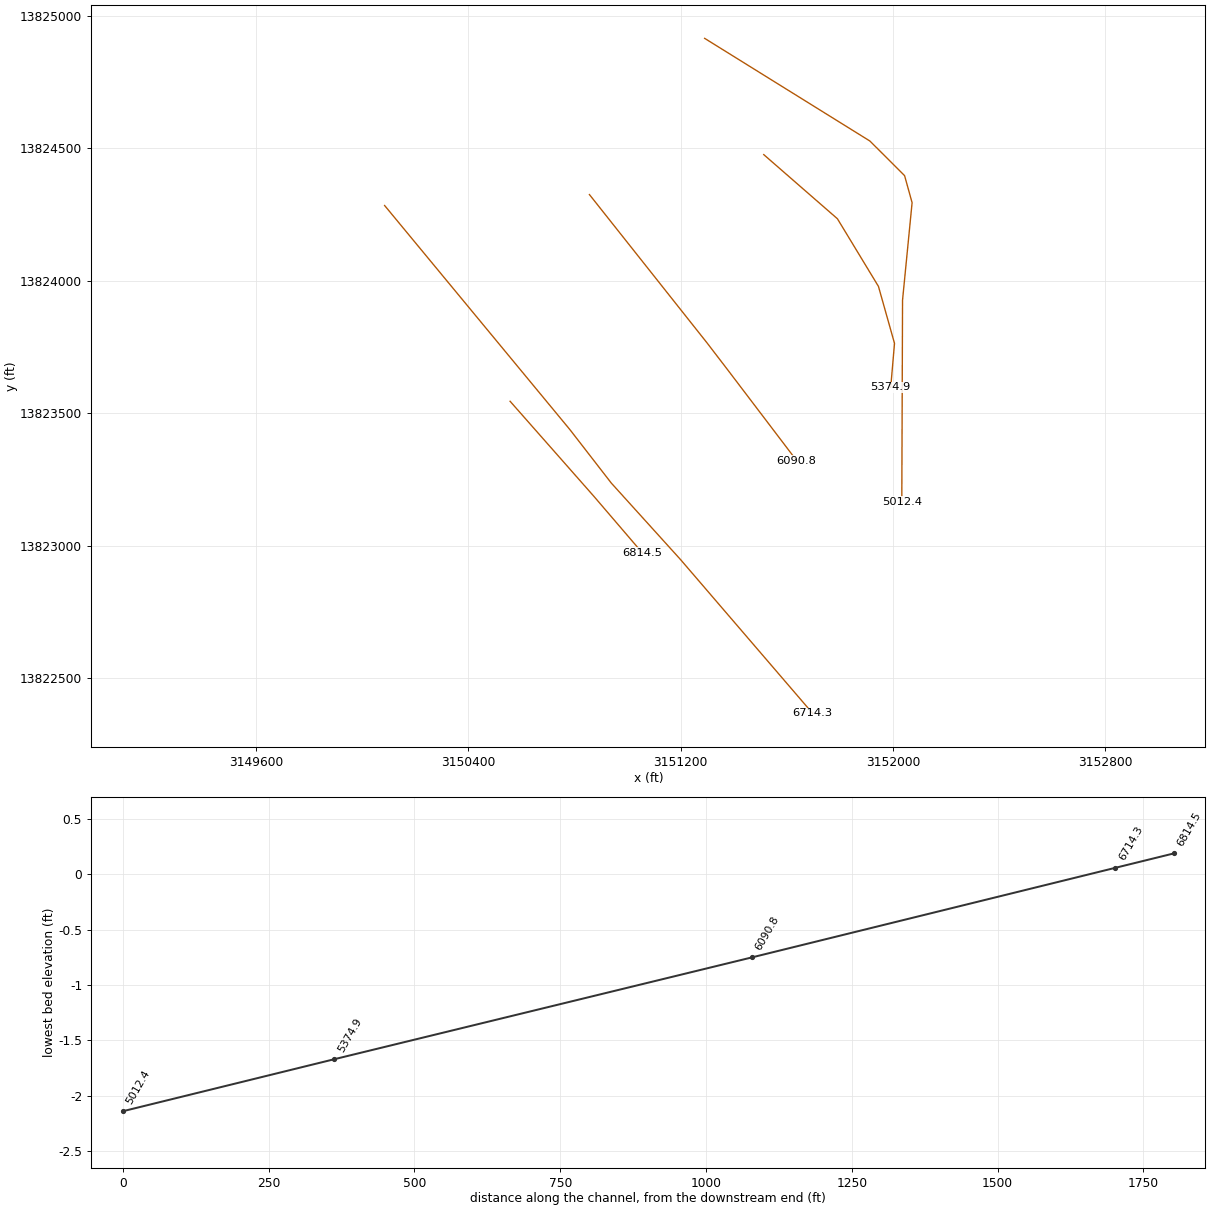
HEC-RAS study C102-00-00.PRJ: C102-00-00

--- C102-00-00.g01 (geometry) --- (continued)

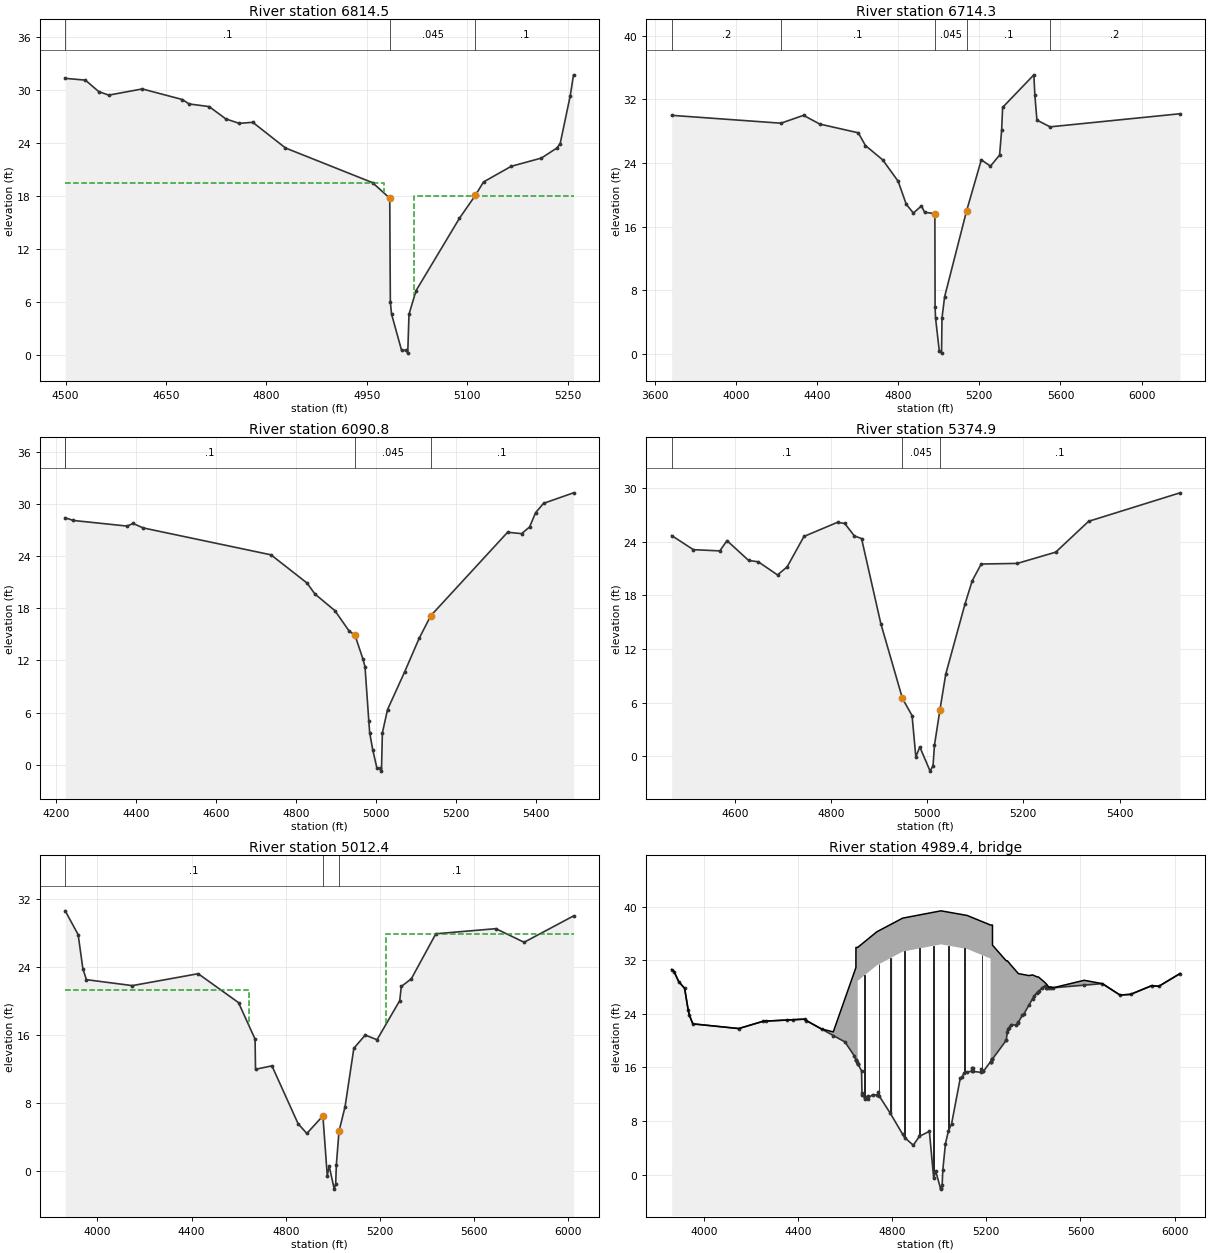
Type RM Length L Ch R = 1 ,6814.5  ,100.2,100.2,100.2
BEGIN DESCRIPTION:
Downstream Section of Bridge/Culvert/Weir
END DESCRIPTION:
XS GIS Cut Line= 3
       3150557.3      13823544.6      3150872.63     13823186.16
      3151056.02     13822971.67
#Sta/Elev= 30
  4499.3   31.33  4529.4   31.13  4549.4   29.83  4564.4   29.43  4614.4   30.13
  4674.4   28.93  4684.4   28.43  4714.4   28.13  4739.4   26.73  4759.4   26.23
 4779.58   26.35 4828.46   23.44 4958.51   19.51 4984.26   17.75 4985.16    5.98
 4986.96    4.62 5001.97      .5  5009.1     .51 5011.15     .19 5013.04     4.6
 5023.62    7.28  5088.4   15.47 5112.26   18.08 5124.41   19.59 5165.72   21.36
 5210.99    22.3  5233.9   23.43  5238.9   23.93  5253.9   29.33  5258.9   31.73
#Mann= 3 , 1 , 0
  4499.3      .1       0 4984.26    .045       0 5112.26      .1       0
#XS Ineff= 2 , 0
       0  4975.5    19.5  5020.4       0      18
Permanent Ineff=
       F       F
Bank Sta=4984.26,5112.26
XS Rating Curve= 0 ,0
Exp/Cntr=0.5,0.3

Type RM Length L Ch R = 1 ,6714.3  ,651.3,623.5,621.9
BEGIN DESCRIPTION:
Cross Section 6714.3-Interpolated
END DESCRIPTION:
XS GIS Cut Line= 5
      3150084.63     13824283.58      3150782.77      13823437.4
      3150938.73     13823235.62      3151199.44     13822946.94
      3151697.09     13822366.35
#Sta/Elev= 30
  3683.4      30  4222.1   29.01  4333.4      30  4413.4    28.9  4603.4    27.8
  4638.4    26.2  4723.4    24.4  4799.8    21.7  4839.8    18.8  4874.8    17.7
  4914.8    18.6  4929.8    17.8  4980.8   17.62  4981.9    5.85  4984.1    4.49
  5002.4     .37  5013.6     .06  5015.9    4.47  5028.8    7.15  5136.9   17.95
  5209.8    24.4  5254.8    23.6  5299.8      25  5309.8    28.1  5314.8      31
  5468.8    35.1  5473.8    32.5  5483.8    29.4  5548.8   28.55  6189.1    30.2
#Mann= 5 , 1 , 0
  3683.4      .2       0  4222.1      .1       0  4980.8    .045       0
  5136.9      .1       0  5548.8      .2       0
Bank Sta=4980.8,5136.9
XS Rating Curve= 0 ,0
Exp/Cntr=0.3,0.1

Type RM Length L Ch R = 1 ,6090.8  ,665.8,715.9,663.4
BEGIN DESCRIPTION:
Cross Section 6090.8-Interpolated
END DESCRIPTION:
XS GIS Cut Line= 4
      3150856.19     13824324.91        3151300.     13823763.99
      3151380.13      13823659.2      3151636.88     13823320.51
#Sta/Elev= 30
  4222.1   28.43  4242.1   28.12  4377.1   27.47  4392.1   27.77  4417.1   27.26
  4737.1   24.16  4827.1   20.92  4847.1   19.65  4897.1   17.73  4932.1   15.42
  4947.4   14.89  4967.4   12.14  4972.4   11.27  4981.9    5.04  4984.1    3.68
  4991.7    1.73  5002.4    -.44  5011.1    -.43  5013.6    -.75  5015.9    3.66
  5028.8    6.34    5072   10.72  5107.8   14.53  5136.9   17.14  5329.3   26.76
  5364.3    26.6  5384.3   27.37  5399.3   29.01  5419.3   30.09  5494.3    31.3
#Mann= 4 , 1 , 0
  4222.1      .2       0  4222.1      .1       0  4947.4    .045       0
  5136.9      .1       0
Bank Sta=4947.4,5136.9
XS Rating Curve= 0 ,0
Exp/Cntr=0.3,0.1

Type RM Length L Ch R = 1 ,5374.9  ,375.5,362.5,327
BEGIN DESCRIPTION:
Cross Section 5374.9-Interpolated
END DESCRIPTION:
XS GIS Cut Line= 5
      3151512.91     13824475.73      3151790.44     13824233.57
      3151945.01      13823978.2      3152005.49     13823763.14
      3151991.23     13823597.39
#Sta/Elev= 30
    4469    24.7    4514   23.12    4569   22.98    4584   24.13    4629   21.91
    4649   21.76    4689   20.29    4709   21.19    4744    24.6  4813.7   26.18
  4828.7   26.05  4848.7   24.66  4863.7   24.36  4903.7   14.85  4948.7    6.46
  4968.7    4.54  4976.5    -.07  4984.8    1.03  5006.2   -1.67  5012.3   -1.05
  5015.2    1.22  5026.4    5.13  5038.7    9.19  5078.7   17.04  5093.7   19.63
  5112.3   21.51  5187.3   21.58  5267.3   22.84  5335.6   26.29  5525.6   29.48
#Mann= 3 , 1 , 0
    4469      .1       0  4948.7    .045       0  5026.4      .1       0
Bank Sta=4948.7,5026.4
XS Rating Curve= 0 ,0
Exp/Cntr=0.5,0.3

Type RM Length L Ch R = 1 ,5012.4  ,46,46,46
BEGIN DESCRIPTION:
Upstream Section of Bridge/Culvert/Weir
END DESCRIPTION:
XS GIS Cut Line= 6
      3151290.18     13824914.66      3151912.94     13824526.92
      3152043.46      13824396.4      3152071.74     13824294.15
      3152035.76     13823926.42      3152032.96     13823164.82
#Sta/Elev= 30
  3863.1   30.61  3918.1   27.81  3938.1   23.81  3953.1   22.51  4148.1   21.81
  4428.1   23.21  4599.4   19.81  4669.8   15.51  4671.7   11.96  4741.4   12.37
  4852.6    5.56  4889.7    4.41    4958    6.48  4976.5    -.54  4984.8     .56
  5006.2   -2.14  5012.3   -1.52  5015.2     .75  5026.4    4.66  5052.1    7.55
  5089.5   14.44    5138   15.99  5187.9   15.44  5284.4   20.04  5291.2   21.71
  5333.7   22.61  5437.9   27.91  5692.9   28.51  5812.9   26.91  6022.9   30.01
#Mann= 3 , 1 , 0
  3863.1      .1       0    4958    .045       0  5026.4      .1       0
#XS Ineff= 2 , 0
       0  4643.2   21.25  5226.3       0    27.9
Permanent Ineff=
       F       F
Bank Sta=4958,5026.4
XS Rating Curve= 0 ,0
Exp/Cntr=0.5,0.3

Type RM Length L Ch R = 3 ,4989.4  ,,,
BEGIN DESCRIPTION:
INTERSTATE ROUTE 610 SOUTHBOUND RAMP
Structure ID: C02-11
END DESCRIPTION:
Bridge Culvert--1,0,-1,-1, 0
Deck Dist Width WeirC Skew NumUp NumDn MinLoCord MaxHiCord MaxSubmerge Is_Ogee
10,26,2.6,0, 53, 53, , , 0.95, 0, 1,1,,
  3863.1  3873.1  3893.1  3918.1  3933.1  3938.1  3953.1  4148.1  4253.1  4428.1
  4434.4  4499.7  4549.7  4599.4  4639.4 4645.89    4646 4653.61  4653.7  4735.1
  4844.5  5007.4  5118.4 5217.99  5218.1  5226.1 5226.21  5284.4  5289.7  5291.2
  5306.2  5326.2  5336.2  5353.7  5358.7  5381.2  5396.2  5403.7  5416.2  5421.2
  5437.9  5447.9  5457.9  5464.7  5474.7  5484.7  5615.6  5692.9  5767.9  5812.9
  5902.9  5932.9  6022.9
    30.6    30.3    28.8    27.8    24.6    23.8    22.5    21.8    22.9   23.21
   23.01   21.74    21.3   26.26   30.25    30.9    33.9    33.9   33.91   36.24
   38.27   39.36   38.67   37.24   37.24   37.24   34.24   31.91    31.9   31.83
    31.2    30.4      30   29.88   29.85    29.7    29.8   29.69    29.5    29.5
      29    28.7   28.34      28      28   27.89      29    28.5    26.8    26.9
    28.2    28.1      30
    30.6    30.3    28.8    27.8    24.6    23.8    22.5    21.8    22.9    23.2
      23   21.73   20.76    19.8    17.7   17.14   17.13   16.55   28.91   31.24
   33.27   34.36   33.67   32.24   16.87   17.25   17.26   20.03   21.33    21.7
    22.4    22.3   22.75    23.8    23.9    25.3   26.23    26.7   27.14   27.31
    27.9    28.1    27.8   27.82   27.85   27.88   28.27    28.5    26.8    26.9
    28.2    28.1      30
  3863.1  3873.1  3893.1  3918.1  3933.1  3938.1  3953.1  4148.1  4253.1  4428.1
  4434.4  4499.7  4549.7  4599.4  4639.4 4645.89    4646 4653.61  4653.7  4735.1
  4844.5  5007.4  5118.4 5217.99  5218.1  5226.1 5226.21  5284.4  5289.7  5291.2
  5306.2  5326.2  5336.2  5353.7  5358.7  5381.2  5396.2  5403.7  5416.2  5421.2
  5437.9  5447.9  5457.9  5464.7  5474.7  5484.7  5615.6  5692.9  5767.9  5812.9
  5902.9  5932.9  6022.9
    30.6    30.3    28.8    27.8    24.6    23.8    22.5    21.8    22.9   23.21
   23.01   21.74    21.3   26.26   30.25    30.9    33.9    33.9   33.91   36.24
   38.27   39.36   38.67   37.24   37.24   37.24   34.24   31.91    31.9   31.83
    31.2    30.4      30   29.88   29.85    29.7    29.8   29.69    29.5    29.5
      29    28.7   28.34      28      28   27.89      29    28.5    26.8    26.9
    28.2    28.1      30
    30.3      30    28.5    27.5    24.3    23.5    22.2    21.5    22.6    22.9
    22.7   21.43   20.46    19.5    17.4   16.84   16.83   16.25   28.61   30.94
   32.97   34.06   33.37   31.94   16.57   16.95   16.96   19.73   21.03    21.4
    22.1      22   22.45    23.5    23.6      25   25.93    26.4   26.84   27.01
    27.6    27.8    27.5   27.52   27.55   27.58   27.97    28.2    26.5    26.6
    27.9    27.8    29.7
Pier Skew, UpSta & Num, DnSta & Num=  ,4682.6, 2 ,4682.6, 2 , 0 , 0 , 0 ,,
     2.5     2.5
   10.43   30.77
     2.5     2.5
   10.13   30.47
Pier Skew, UpSta & Num, DnSta & Num=  ,4744.1, 2 ,4744.1, 2 , 0 , 0 , 0 ,,
     2.5     2.5
   10.72   32.43
     2.5     2.5
   10.42   32.13
Pier Skew, UpSta & Num, DnSta & Num=  ,4791.7, 2 ,4791.7, 2 , 0 , 0 , 0 ,,
     2.5     2.5
    8.11   33.31
     2.5     2.5
    7.81   33.01
Pier Skew, UpSta & Num, DnSta & Num=  ,4852.6, 2 ,4852.6, 2 , 0 , 0 , 0 ,,
     2.5     2.5
    4.51   34.33
     2.5     2.5
    4.21   34.03
Pier Skew, UpSta & Num, DnSta & Num=  ,4915.5, 2 ,4915.5, 2 , 0 , 0 , 0 ,,
     2.5     2.5
    4.66   34.76
     2.5     2.5
    4.36   34.46
Pier Skew, UpSta & Num, DnSta & Num=  ,4976.5, 2 ,4976.5, 2 , 0 , 0 , 0 ,,
     2.5     2.5
   -1.38   35.16
     2.5     2.5
   -1.68   34.86
Pier Skew, UpSta & Num, DnSta & Num=  ,5039, 2 ,5039, 2 , 0 , 0 , 0 ,,
     2.5     2.5
    5.35   35.17
     2.5     2.5
    5.05   34.87
Pier Skew, UpSta & Num, DnSta & Num=  ,5106.5, 2 ,5106.5, 2 , 0 , 0 , 0 ,,
     2.5     2.5
   14.15   34.75
     2.5     2.5
   13.85   34.45
Pier Skew, UpSta & Num, DnSta & Num=  ,5181.5, 2 ,5181.5, 2 , 0 , 0 , 0 ,,
     2.5     2.5
   14.51   33.78
     2.5     2.5
   14.21   33.48
Abutment Skew #Up #Dn= , 2 , 2
  4653.5  4671.7
   28.91   11.95
  4653.5  4671.7
   28.61   11.65
Abutment Skew #Up #Dn= , 2 , 2
  5187.9 5218.19
   15.43   32.24
  5187.9 5218.19
   15.13   31.94
BR Coef= 1 , 1 , 0 ,1.25, 0 ,,,0.8,0,2,0,
WSPro=,,,, 1 ,,,, 0 ,,,, 0 ,,,,-1 ,-1 ,-1 , 0 , 0 , 0 , 0 , 0
BR U #Sta/Elev= 102
  3863.1    30.6  3873.1    30.3  3893.1    28.8  3918.1    27.8  3933.1    24.6
  3938.1    23.8  3953.1    22.5  4148.1    21.8  4253.1    22.9  4263.1    22.9
  4354.4   23.07  4379.7   23.11  4428.1    23.2  4434.4      23  4499.7   21.73
  4549.7   20.76  4599.4    19.8  4639.4    17.7 4645.89   17.14    4646   17.13
 4646.11   17.12  4649.8    16.8  4653.5   16.56 4653.61   16.55  4653.7   16.55
  4669.8    15.5  4671.6   12.14  4671.7   11.95  4682.6   11.48  4686.1   11.35
  4695.4   11.79  4695.7   11.33  4716.7   11.95  4735.1    11.9    4741   11.89
  4741.4   12.36  4744.1   11.79  4791.7    9.18  4844.5    6.03  4852.6    5.55
  4889.7     4.4  4915.5    5.72    4958    6.47  4976.5    -.55  4984.8     .55
  5006.2   -2.15  5007.4   -2.03  5012.3   -1.53  5015.2     .74  5026.4    4.65
    5039    6.54  5052.1    7.54  5089.5   14.43  5095.7   14.53  5106.5   15.23
  5118.4   15.31  5137.2   15.44    5138   15.98  5142.1   15.98  5142.7   15.41
  5178.1   15.27  5178.4   15.79  5181.5   15.53  5187.8   15.43  5187.9   15.43
 5217.99   16.86  5218.1   16.87  5218.2   16.87 5225.99   17.25  5226.1   17.25
 5226.21   17.26  5284.4   20.03  5284.7    20.1  5289.7   21.33  5291.2    21.7
  5296.2   21.93  5306.2    22.4  5326.2    22.3  5333.7    22.6  5336.2   22.75
  5353.7    23.8  5358.7    23.9  5381.2    25.3  5396.2   26.23  5403.7    26.7
  5416.2   27.14  5421.2   27.31  5424.7   27.44  5437.9    27.9  5447.9    28.1
  5454.7    27.9  5457.9    27.8  5464.7   27.82  5474.7   27.85  5484.7   27.88
  5615.6   28.27  5692.9    28.5  5767.9    26.8  5812.9    26.9  5902.9    28.2
  5932.9    28.1  6022.9      30
BR U #Mann= 3
  3863.1      .1    4958    .045  5026.4      .1
BR U Banks=4958,5026.4
BR D #Sta/Elev= 102
  3863.1    30.3  3873.1      30  3893.1    28.5  3918.1    27.5  3933.1    24.3
  3938.1    23.5  3953.1    22.2  4148.1    21.5  4253.1    22.6  4263.1    22.6
  4354.4   22.77  4379.7   22.81  4428.1    22.9  4434.4    22.7  4499.7   21.43
  4549.7   20.46  4599.4    19.5  4639.4    17.4 4645.89   16.84    4646   16.83
 4646.11   16.82  4649.8    16.5  4653.5   16.26 4653.61   16.25  4653.7   16.25
  4669.8    15.2  4671.6   11.84  4671.7   11.65  4682.6   11.18  4686.1   11.05
  4695.4   11.49  4695.7   11.03  4716.7   11.65  4735.1    11.6    4741   11.59
  4741.4   12.06  4744.1   11.49  4791.7    8.88  4844.5    5.73  4852.6    5.25
  4889.7     4.1  4915.5    5.42    4958    6.17  4976.5    -.85  4984.8     .25
  5006.2   -2.45  5007.4   -2.33  5012.3   -1.83  5015.2     .44  5026.4    4.35
    5039    6.24  5052.1    7.24  5089.5   14.13  5095.7   14.23  5106.5   14.93
  5118.4   15.01  5137.2   15.14    5138   15.68  5142.1   15.68  5142.7   15.11
  5178.1   14.97  5178.4   15.49  5181.5   15.23  5187.8   15.13  5187.9   15.13
 5217.99   16.56  5218.1   16.57  5218.2   16.57 5225.99   16.95  5226.1   16.95
 5226.21   16.96  5284.4   19.73  5284.7    19.8  5289.7   21.03  5291.2    21.4
  5296.2   21.63  5306.2    22.1  5326.2      22  5333.7    22.3  5336.2   22.45
  5353.7    23.5  5358.7    23.6  5381.2      25  5396.2   25.93  5403.7    26.4
  5416.2   26.84  5421.2   27.01  5424.7   27.14  5437.9    27.6  5447.9    27.8
  5454.7    27.6  5457.9    27.5  5464.7   27.52  5474.7   27.55  5484.7   27.58
  5615.6   27.97  5692.9    28.2  5767.9    26.5  5812.9    26.6  5902.9    27.9
  5932.9    27.8  6022.9    29.7
BR D #Mann= 3
  3863.1      .1    4958    .045  5026.4      .1
BR D Banks=4958,5026.4
BC Design=,, 0 ,, 0 ,,,,,,
BC HTab HWMax=30.61
BC Use User HTab Curves=0
BC User HTab FreeFlow(D)= 0