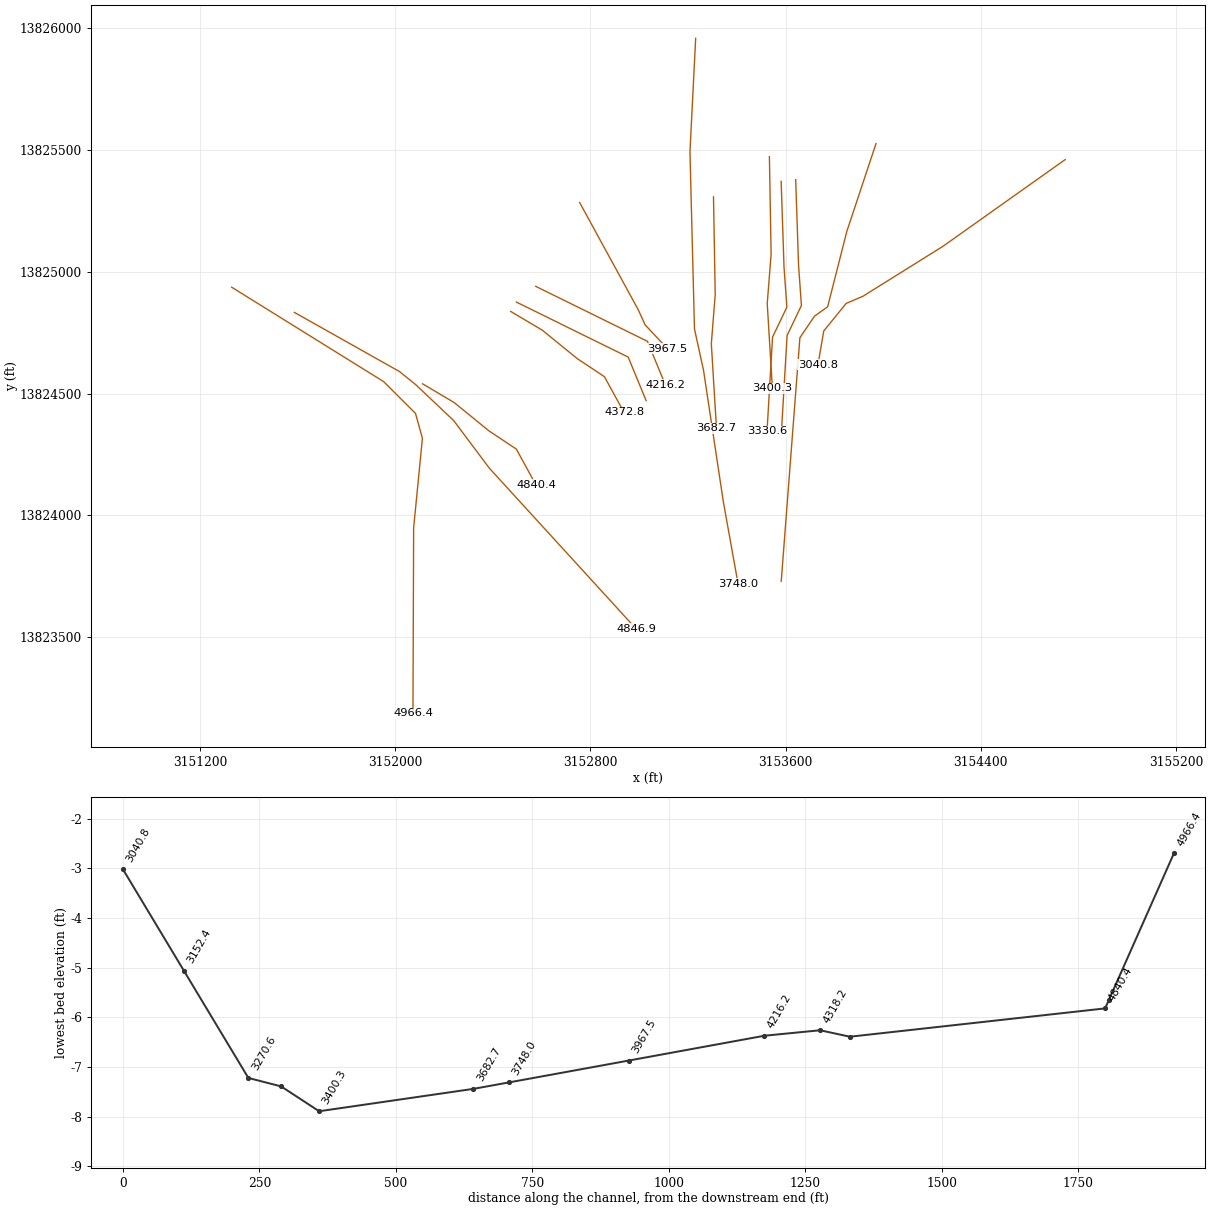
HEC-RAS study C102-00-00.PRJ: C102-00-00

--- C102-00-00.g01 (geometry) --- (continued)

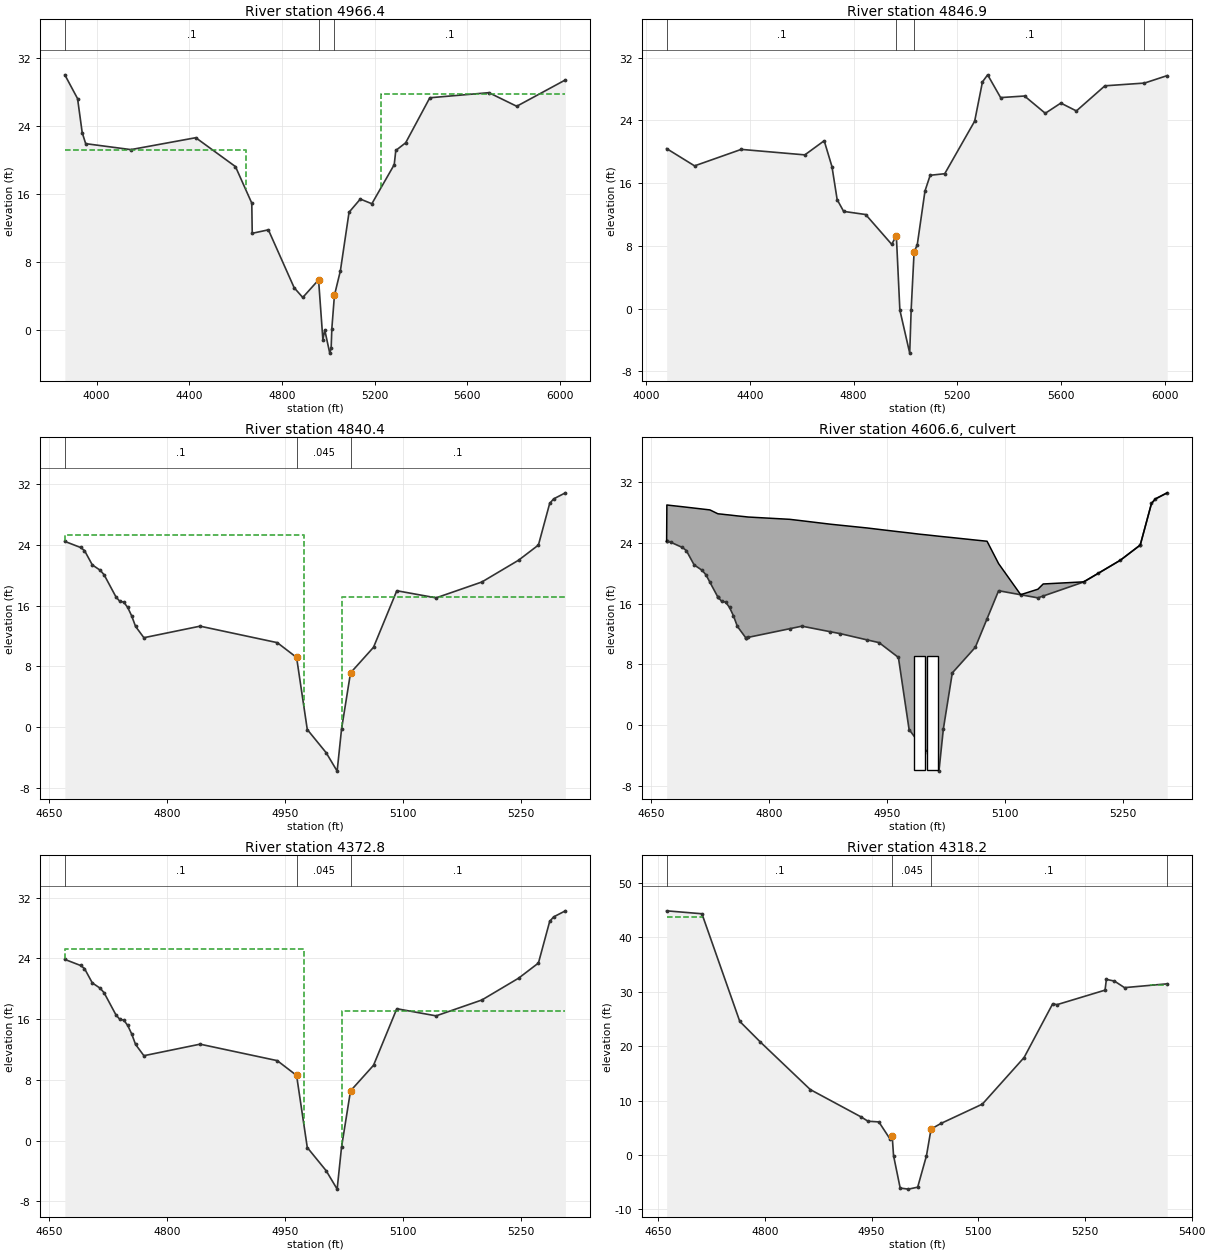
Type RM Length L Ch R = 1 ,4966.4  ,119.5,119.5,119.5
BEGIN DESCRIPTION:
Downstream Section of Bridge/Culvert/Weir
END DESCRIPTION:
XS GIS Cut Line= 6
      3151330.39       13824937.      3151953.16     13824549.26
      3152083.68     13824418.74      3152111.96     13824316.49
      3152075.98     13823948.76      3152073.18     13823187.16
#Sta/Elev= 30
  3863.1   30.05  3918.1   27.25  3938.1   23.25  3953.1   21.95  4148.1   21.25
  4428.1   22.65  4599.4   19.25  4669.8   14.95  4671.7    11.4  4741.4   11.81
  4852.6       5  4889.7    3.85    4958    5.92  4976.5    -1.1  4984.8       0
  5006.2    -2.7  5012.3   -2.08  5015.2     .19  5026.4     4.1  5052.1    6.99
  5089.5   13.88    5138   15.43  5187.9   14.88  5284.4   19.48  5291.2   21.15
  5333.7   22.05  5437.9   27.35  5692.9   27.95  5812.9   26.35  6022.9   29.45
#Mann= 3 , 1 , 0
  3863.1      .1       0    4958    .045       0  5026.4      .1       0
#XS Ineff= 2 , 0
       0  4643.2    21.2  5226.3       0    27.8
Permanent Ineff=
       F       F
Bank Sta=4958,5026.4
XS Rating Curve= 0 ,0
Exp/Cntr=0.5,0.3

Type RM Length L Ch R = 1 ,4846.9  ,6.2,6.5,8.1
BEGIN DESCRIPTION:
Cross Section 4846.9-Interpolated
END DESCRIPTION:
XS GIS Cut Line= 6
      3151587.49      13824833.5      3152017.72     13824590.83
      3152083.55     13824537.72        3152240.      13824389.5
      3152386.16     13824193.93       3152987.3     13823534.51
#Sta/Elev= 30
  4078.5    20.4  4186.3    18.2  4366.3    20.3  4611.7    19.6  4686.3    21.4
  4716.3    18.1  4736.3    13.9  4761.3    12.4  4846.3      12  4946.8     8.2
  4964.6    9.32  4978.2    -.18  5016.2   -5.66  5021.8    -.11  5033.2    7.28
  5045.1     8.1  5075.1      15  5095.1      17  5151.3    17.2  5266.8    23.9
  5296.8    28.9  5316.8    29.8  5366.8    26.9  5459.1    27.1  5539.1    24.9
  5599.1    26.2  5659.1    25.2  5769.1    28.4  5921.8   28.75  6009.4    29.7
#Mann= 4 , 1 , 0
  4078.5      .1       0  4964.6    .045       0  5033.2      .1       0
  5921.8      .2       0
Bank Sta=4964.6,5033.2
XS Rating Curve= 0 ,0
Exp/Cntr=0.5,0.3

Type RM Length L Ch R = 1 ,4840.4  ,467.6,467.6,467.6
BEGIN DESCRIPTION:
Upstream Section of Bridge/Culvert/Weir
END DESCRIPTION:
XS GIS Cut Line= 5
      3152112.62     13824540.25      3152241.86     13824463.45
      3152385.26     13824346.61      3152496.79     13824272.25
      3152577.17     13824125.25
#Sta/Elev= 30
  4669.7   24.45  4689.7   23.65  4694.7   23.25  4704.7   21.35  4714.7   20.65
  4719.7   20.05  4734.7   17.15  4739.7   16.55  4744.7   16.45  4749.7   15.75
  4754.7   14.65  4759.7   13.25  4770.3   11.76  4841.8   13.28    4940   11.11
  4964.6    9.16  4978.2    -.34  5002.2   -3.39  5016.2   -5.82  5021.8    -.27
  5033.2    7.12  5062.5    10.5  5092.1   17.95  5142.1   17.01  5200.3    19.1
    5247   21.97  5272.3   23.97  5286.6   29.45  5291.6   30.05  5306.6   30.85
#Mann= 3 , 1 , 0
  4669.7      .1       0  4964.6    .045       0  5033.2      .1       0
#XS Ineff= 2 , 0
       0    4974    25.3  5022.1       0    17.1
Permanent Ineff=
       F       F
Bank Sta=4964.6,5033.2
XS Rating Curve= 0 ,0
Exp/Cntr=0.5,0.3

Type RM Length L Ch R = 2 ,4606.6  ,,,
BEGIN DESCRIPTION:
STATE ROUTE 225 EASTBOUND RAMP
Structure ID: C02-10
END DESCRIPTION:
Bridge Culvert--1,0,-1,-1, 0
Deck Dist Width WeirC Skew NumUp NumDn MinLoCord MaxHiCord MaxSubmerge Is_Ogee
10,447.6,3,0, 47, 47, , , 0.95, 0, 1,1,,
  4669.7    4670  4674.7  4689.7  4694.7  4704.7  4714.7  4719.7  4724.8  4734.7
  4734.8  4739.7  4744.7  4749.7  4754.7  4759.7  4770.3  4770.7  4773.7  4826.2
  4841.8  4877.8  4890.8  4924.8    4940  4964.6  4978.2  4989.2  4991.7  5002.2
  5016.2  5021.8  5033.2  5062.5  5077.4  5092.1  5120.2  5142.1  5148.8  5200.3
  5218.9    5247  5272.2  5272.3  5286.6  5291.6  5306.6
    24.2      29   28.94   28.77   28.71   28.59   28.47   28.41   28.35   27.85
   27.84   27.79   27.73   27.68   27.62   27.56   27.45   27.44   27.41   27.11
   26.92   26.47   26.33   25.97   25.78   25.48   25.32   25.18   25.15   25.04
   24.88   24.82    24.7   24.38   24.22   21.27   17.18    17.9   18.59   18.87
      20   21.72   23.71   23.72    29.2    29.8    30.6
    24.2   24.19    24.1    23.4      23    21.1    20.4    19.8   18.81    16.9
   16.89    16.3    16.2    15.5    14.4      13   11.51    11.5   11.56   12.69
   13.03    12.3   12.04   11.22   10.86    8.91    -.59   -2.11    -2.4   -3.64
   -6.07    -.52    6.87   10.25      14    17.7   17.17   16.76      17   18.85
   19.99   21.72   23.71   23.72    29.2    29.8    30.6
  4669.7    4670  4674.7  4689.7  4694.7  4704.7  4714.7  4719.7  4724.8  4734.7
  4734.8  4739.7  4744.7  4749.7  4754.7  4759.7  4770.3  4770.7  4773.7  4826.2
  4841.8  4877.8  4890.8  4924.8    4940  4964.6  4978.2  4989.2  4991.7  5002.2
  5016.2  5021.8  5033.2  5062.5  5077.4  5092.1  5120.2  5142.1  5148.8  5200.3
  5218.9    5247  5272.2  5272.3  5286.6  5291.6  5306.6
    24.2      29   28.94   28.77   28.71   28.59   28.47   28.41   28.35   27.85
   27.84   27.79   27.73   27.68   27.62   27.56   27.45   27.44   27.41   27.11
   26.92   26.47   26.33   25.97   25.78   25.48   25.32   25.18   25.15   25.04
   24.88   24.82    24.7   24.38   24.22   21.27   17.18    17.9   18.59   18.87
      20   21.72   23.71   23.72    29.2    29.8    30.6
   23.86   23.85   23.76   23.06   22.66   20.76   20.06   19.46   18.47   16.56
   16.55   15.96   15.86   15.16   14.06   12.66   11.17   11.16   11.22   12.35
   12.69   11.96    11.7   10.88   10.52    8.57    -.93   -2.45   -2.74   -3.98
   -6.41    -.86    6.53    9.91   13.66   17.36   16.83   16.42   16.66   18.51
   19.65   21.38   23.37   23.38   28.86   29.46   30.26
BR Coef= 1 , 0 , 0 ,1.25, 0 ,,,0.8,-1,2,0,
WSPro=,,,, 1 ,,,, 0 ,,,, 0 ,,,,-1 ,-1 ,-1 , 0 , 0 , 0 , 0 , 0
Culvert=2,15,15,447.6,0.015,0.4,1,8,1,-5.88,4991.4,-6.8,4991.4,Culvert #1  , 0 ,10
Culvert Bottom n=0.015
Culvert=2,15,15,447.6,0.015,0.4,1,8,1,-5.88,5007.9,-6.8,5007.9,Culvert #2  , 0 ,10
Culvert Bottom n=0.015
BR U #Sta/Elev= 47
  4669.7    24.2    4670   24.19  4674.7    24.1  4689.7    23.4  4694.7      23
  4704.7    21.1  4714.7    20.4  4719.7    19.8  4724.8   18.81  4734.7    16.9
  4734.8   16.89  4739.7    16.3  4744.7    16.2  4749.7    15.5  4754.7    14.4
  4759.7      13  4770.3   11.51  4770.7    11.5  4773.7   11.56  4826.2   12.69
  4841.8   13.03  4877.8    12.3  4890.8   12.04  4924.8   11.22    4940   10.86
  4964.6    8.91  4978.2    -.59  4989.2   -2.11  4991.7    -2.4  5002.2   -3.64
  5016.2   -6.07  5021.8    -.52  5033.2    6.87  5062.5   10.25  5077.4      14
  5092.1    17.7  5120.2   17.17  5142.1   16.76  5148.8      17  5200.3   18.85
  5218.9   19.99    5247   21.72  5272.2   23.71  5272.3   23.72  5286.6    29.2
  5291.6    29.8  5306.6    30.6
BR U #Mann= 3
  4669.7      .1  4964.6    .045  5033.2      .1
BR U Banks=4964.6,5033.2
BR D #Sta/Elev= 47
  4669.7   23.86    4670   23.85  4674.7   23.76  4689.7   23.06  4694.7   22.66
  4704.7   20.76  4714.7   20.06  4719.7   19.46  4724.8   18.47  4734.7   16.56
  4734.8   16.55  4739.7   15.96  4744.7   15.86  4749.7   15.16  4754.7   14.06
  4759.7   12.66  4770.3   11.17  4770.7   11.16  4773.7   11.22  4826.2   12.35
  4841.8   12.69  4877.8   11.96  4890.8    11.7  4924.8   10.88    4940   10.52
  4964.6    8.57  4978.2    -.93  4989.2   -2.45  4991.7   -2.74  5002.2   -3.98
  5016.2   -6.41  5021.8    -.86  5033.2    6.53  5062.5    9.91  5077.4   13.66
  5092.1   17.36  5120.2   16.83  5142.1   16.42  5148.8   16.66  5200.3   18.51
  5218.9   19.65    5247   21.38  5272.2   23.37  5272.3   23.38  5286.6   28.86
  5291.6   29.46  5306.6   30.26
BR D #Mann= 3
  4669.7      .1  4964.6    .045  5033.2      .1
BR D Banks=4964.6,5033.2
BC Design=,, 0 ,, 0 ,,,,,,
BC HTab HWMax=30.85
BC Use User HTab Curves=0
BC User HTab FreeFlow(D)= 0

Type RM Length L Ch R = 1 ,4372.8  ,54.6,54.6,54.6
BEGIN DESCRIPTION:
Downstream Section of Bridge/Culvert/Weir
END DESCRIPTION:
XS GIS Cut Line= 5
      3152473.56     13824837.52       3152602.8     13824760.73
       3152746.2     13824643.89      3152857.73     13824569.53
      3152938.11     13824422.52
#Sta/Elev= 30
  4669.7   23.88  4689.7   23.08  4694.7   22.68  4704.7   20.78  4714.7   20.08
  4719.7   19.48  4734.7   16.58  4739.7   15.98  4744.7   15.88  4749.7   15.18
  4754.7   14.08  4759.7   12.68  4770.3   11.19  4841.8   12.71    4940   10.54
  4964.6    8.59  4978.2    -.91  5002.2   -3.96  5016.2   -6.39  5021.8    -.84
  5033.2    6.55  5062.5    9.93  5092.1   17.38  5142.1   16.44  5200.3   18.53
    5247    21.4  5272.3    23.4  5286.6   28.88  5291.6   29.48  5306.6   30.28
#Mann= 3 , 1 , 0
  4669.7      .1       0  4964.6    .045       0  5033.2      .1       0
#XS Ineff= 2 , 0
       0    4974    25.3  5022.1       0    17.1
Permanent Ineff=
       F       F
Bank Sta=4964.6,5033.2
XS Rating Curve= 0 ,0
Exp/Cntr=0.5,0.3

Type RM Length L Ch R = 1 ,4318.2  ,102,102,102
BEGIN DESCRIPTION:
Upstream Section of Bridge/Culvert/Weir
END DESCRIPTION:
XS GIS Cut Line= 3
      3152497.22     13824875.76      3152955.07     13824649.97
      3153028.51     13824471.27
#Sta/Elev= 26
  4661.9    44.9 4711.52   44.36 4764.74   24.57 4793.69   20.78 4863.88   12.04
 4935.06    7.03 4945.06    6.22 4960.23     6.1 4976.14    2.92 4979.01    3.52
 4980.89    -.09 4990.24   -6.07 5001.89   -6.26 5014.84    -5.9 5027.22     -.1
 5033.62    4.78 5047.48    5.81 5105.78    9.37 5164.41   17.93 5204.67   27.82
 5210.66   27.65 5278.23   30.32 5280.11    32.3 5291.51   31.98  5305.6   30.78
  5365.6   31.48
#Mann= 4 , 1 , 0
  4661.9      .1       0 4979.01    .045       0 5033.62      .1       0
  5365.6      .2       0
#XS Ineff= 2 , 0
       0  4713.1   43.79    5341       0    31.2
Permanent Ineff=
       F       F
Bank Sta=4979.01,5033.62
XS Rating Curve= 0 ,0
Exp/Cntr=0.5,0.3

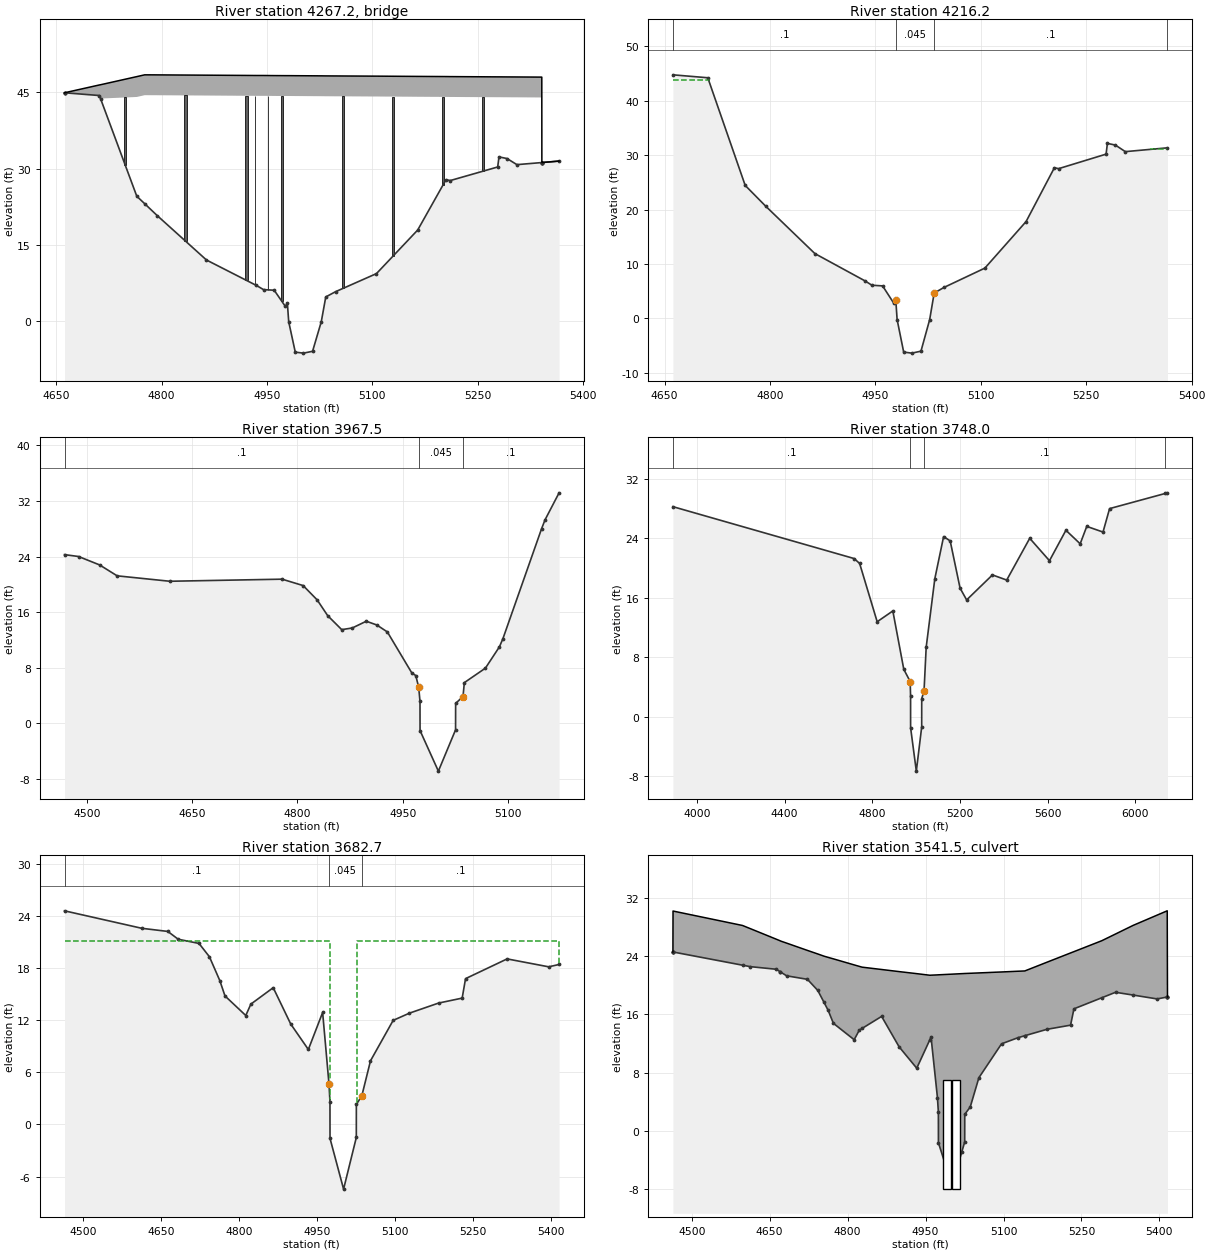
Type RM Length L Ch R = 3 ,4267.2  ,,,
BEGIN DESCRIPTION:
STATE ROUTE 225 WESTBOUND RAMP, SKEW ANGLE OF 35 DEGREES
Structure ID: C02-9
END DESCRIPTION:
Bridge Culvert--1,0,-1,-1, 0
Deck Dist Width WeirC Skew NumUp NumDn MinLoCord MaxHiCord MaxSubmerge Is_Ogee
10,82,2.6,0, 34, 34, , , 0.95, 0, 1,1,,
  4661.9 4662.01  4662.1 4711.52  4713.1 4764.74    4776 4793.69 4863.88 4935.06
 4945.06 4960.23 4976.14 4979.01 4980.89 4990.24 5001.89 5014.84 5027.22 5033.62
 5047.48 5105.78 5164.41 5204.67 5210.66 5278.23 5280.11 5291.51  5305.6    5341
  5341.1 5341.49  5341.6  5365.6
   44.92   44.92   44.93   46.46    46.5    48.1   48.45   48.44   48.38   48.32
   48.32    48.3   48.29   48.29   48.29   48.28   48.27   48.26   48.25   48.24
   48.23   48.19   48.14   48.11    48.1   48.05   48.05   48.04   48.03      48
   31.21   31.22   31.22    31.5
   44.92   44.92   44.92   44.38   43.79    44.1   44.45   44.44   44.38   44.32
   44.32    44.3   44.29   44.29   44.29   44.28   44.27   44.26   44.25   44.24
   44.23   44.19   44.14   44.11    44.1   44.05   44.05   44.04   44.03      44
   31.21   31.22   31.22    31.5
  4661.9 4662.01  4662.1 4711.52  4713.1 4764.74    4776 4793.69 4863.88 4935.06
 4945.06 4960.23 4976.14 4979.01 4980.89 4990.24 5001.89 5014.84 5027.22 5033.62
 5047.48 5105.78 5164.41 5204.67 5210.66 5278.23 5280.11 5291.51  5305.6    5341
  5341.1 5341.49  5341.6  5365.6
   44.92   44.92   44.93   46.46    46.5    48.1   48.45   48.44   48.38   48.32
   48.32    48.3   48.29   48.29   48.29   48.28   48.27   48.26   48.25   48.24
   48.23   48.19   48.14   48.11    48.1   48.05   48.05   48.04   48.03      48
   31.21   31.22   31.22    31.5
   44.81   44.81   44.81   44.27   43.68   43.99   44.34   44.33   44.27   44.21
   44.21   44.19   44.18   44.18   44.18   44.17   44.16   44.15   44.14   44.13
   44.12   44.08   44.03      44   43.99   43.94   43.94   43.93   43.92   43.89
    31.1   31.11   31.11   31.39
Pier Skew, UpSta & Num, DnSta & Num=  ,4748.4, 2 ,4748.4, 2 , 0 , 0 , 0 ,,
       3       3
   29.11   45.01
       3       3
      29    44.9
Pier Skew, UpSta & Num, DnSta & Num=  ,4834, 2 ,4834, 2 , 0 , 0 , 0 ,,
       3       3
   14.59   45.41
       3       3
   14.48    45.3
Pier Skew, UpSta & Num, DnSta & Num=  ,4920.8, 2 ,4920.8, 2 , 0 , 0 , 0 ,,
       3       3
    6.95   45.33
       3       3
    6.84   45.22
Pier Skew, UpSta & Num, DnSta & Num=  ,4933, 2 ,4933, 2 , 0 , 0 , 0 ,,
       1       1
    6.16   45.32
       1       1
    6.05   45.21
Pier Skew, UpSta & Num, DnSta & Num=  ,4951.5, 2 ,4951.5, 2 , 0 , 0 , 0 ,,
       1       1
    5.19   45.31
       1       1
    5.08    45.2
Pier Skew, UpSta & Num, DnSta & Num=  ,4970.9, 2 ,4970.9, 2 , 0 , 0 , 0 ,,
       3       3
    2.69   45.29
       3       3
    2.58   45.18
Pier Skew, UpSta & Num, DnSta & Num=  ,5057.9, 2 ,5057.9, 2 , 0 , 0 , 0 ,,
       3       3
    5.37   45.22
       3       3
    5.26   45.11
Pier Skew, UpSta & Num, DnSta & Num=  ,5129, 2 ,5129, 2 , 0 , 0 , 0 ,,
       3       3
   11.56   45.17
       3       3
   11.45   45.06
Pier Skew, UpSta & Num, DnSta & Num=  ,5200.5, 2 ,5200.5, 2 , 0 , 0 , 0 ,,
       3       3
   25.45   45.11
       3       3
   25.34      45
Pier Skew, UpSta & Num, DnSta & Num=  ,5256.9, 2 ,5256.9, 2 , 0 , 0 , 0 ,,
       3       3
   28.44   45.07
       3       3
   28.33   44.96
Abutment Skew #Up #Dn= , 2 , 2
  4661.9  4713.1
   44.92   43.79
  4661.9  4713.1
   44.81   43.68
BR Coef= 1 , 1 , 0 ,1.25, 0 ,,,0.8,0,2,0,
WSPro=,,,, 1 ,,,, 0 ,,,, 0 ,,,,-1 ,-1 ,-1 , 0 , 0 , 0 , 0 , 0
BR U #Sta/Elev= 34
  4661.9   44.92 4662.01   44.92  4662.1   44.92 4711.52   44.38  4713.1   43.79
 4764.74   24.59    4776   23.12 4793.69    20.8 4863.88   12.06 4935.06    7.05
 4945.06    6.24 4960.23    6.12 4976.14    2.94 4979.01    3.54 4980.89    -.07
 4990.24   -6.05 5001.89   -6.24 5014.84   -5.88 5027.22    -.08 5033.62     4.8
 5047.48    5.83 5105.78    9.39 5164.41   17.95 5204.67   27.84 5210.66   27.67
 5278.23   30.34 5280.11   32.32 5291.51      32  5305.6    30.8    5341   31.21
  5341.1   31.21 5341.49   31.22  5341.6   31.22  5365.6    31.5
BR U #Mann= 4
  4661.9      .1 4979.01    .045 5033.62      .1  5365.6      .2
BR U Banks=4979.01,5033.62
BR D #Sta/Elev= 34
  4661.9   44.81 4662.01   44.81  4662.1   44.81 4711.52   44.27  4713.1   43.68
 4764.74   24.48    4776   23.01 4793.69   20.69 4863.88   11.95 4935.06    6.94
 4945.06    6.13 4960.23    6.01 4976.14    2.83 4979.01    3.43 4980.89    -.18
 4990.24   -6.16 5001.89   -6.35 5014.84   -5.99 5027.22    -.19 5033.62    4.69
 5047.48    5.72 5105.78    9.28 5164.41   17.84 5204.67   27.73 5210.66   27.56
 5278.23   30.23 5280.11   32.21 5291.51   31.89  5305.6   30.69    5341    31.1
  5341.1    31.1 5341.49   31.11  5341.6   31.11  5365.6   31.39
BR D #Mann= 4
  4661.9      .1 4979.01    .045 5033.62      .1  5365.6      .2
BR D Banks=4979.01,5033.62
BC Design=,, 0 ,, 0 ,,,,,,
BC HTab HWMax=44.9
BC Use User HTab Curves=0
BC User HTab FreeFlow(D)= 0

Type RM Length L Ch R = 1 ,4216.2  ,248.7,248.7,248.7
BEGIN DESCRIPTION:
Downstream Section of Bridge/Culvert/Weir
END DESCRIPTION:
XS GIS Cut Line= 3
        3152576.     13824940.55      3153033.85     13824714.77
      3153107.28     13824536.06
#Sta/Elev= 26
  4661.9   44.79 4711.52   44.25 4764.74   24.46 4793.69   20.67 4863.88   11.93
 4935.06    6.92 4945.06    6.11 4960.23    5.99 4976.14    2.81 4979.01    3.41
 4980.89     -.2 4990.24   -6.18 5001.89   -6.37 5014.84   -6.01 5027.22    -.21
 5033.62    4.67 5047.48     5.7 5105.78    9.26 5164.41   17.82 5204.67   27.71
 5210.66   27.54 5278.23   30.21 5280.11   32.19 5291.51   31.87  5305.6   30.67
  5365.6   31.37
#Mann= 4 , 1 , 0
  4661.9      .1       0 4979.01    .045       0 5033.62      .1       0
  5365.6      .2       0
#XS Ineff= 2 , 0
       0  4713.1   43.79    5341       0    31.2
Permanent Ineff=
       F       F
Bank Sta=4979.01,5033.62
XS Rating Curve= 0 ,0
Exp/Cntr=0.5,0.3

Type RM Length L Ch R = 1 ,3967.5  ,235.4,219.5,200.7
BEGIN DESCRIPTION:
Cross Section 3967.5-Interpolated
END DESCRIPTION:
XS GIS Cut Line= 4
      3152756.04     13825284.71      3152995.78     13824845.37
      3153024.42     13824782.36      3153116.53     13824683.67
#Sta/Elev= 30
  4468.1   24.27  4488.1      24  4518.1   22.79  4543.1   21.22  4618.1   20.44
  4778.1   20.74  4808.1   19.82  4828.1   17.76  4843.1   15.49  4863.1   13.48
  4878.1   13.72  4898.1   14.69  4913.1   14.15  4928.1   13.15  4963.1    7.23
  4968.6    6.88  4972.8    5.17  4974.6    3.16  4974.7   -1.04  5000.8   -6.87
  5025.3    -.93  5025.4    2.87  5035.9    3.86  5037.8    5.86  5067.8    7.94
  5087.8   11.01  5092.8   12.19  5147.8   27.98  5152.8   29.28  5172.8   33.16
#Mann= 3 , 1 , 0
  4468.1      .1       0  4972.8    .045       0  5035.9      .1       0
Bank Sta=4972.8,5035.9
XS Rating Curve= 0 ,0
Exp/Cntr=0.3,0.1

Type RM Length L Ch R = 1 ,3748.0  ,75,65.3,53.2
BEGIN DESCRIPTION:
Cross Section 3748.0-Interpolated
END DESCRIPTION:
XS GIS Cut Line= 6
      3153231.51     13825958.78      3153208.15     13825493.09
       3153226.6     13824765.54       3153263.5     13824596.83
      3153345.22     13824053.81      3153405.07     13823720.12
#Sta/Elev= 30
    3891   28.22  4717.3   21.25  4742.3   20.59  4822.3   12.76  4893.7   14.21
  4943.7    6.36  4972.8    4.73  4974.6    2.72  4974.7   -1.48  5000.8   -7.31
  5025.3   -1.37  5025.4    2.43  5035.9    3.42  5045.8    9.34  5085.2   18.55
  5125.2    24.2  5155.2   23.62  5200.2   17.28  5230.2   15.69  5347.9   19.05
  5412.9   18.36  5517.9   23.97  5607.9   20.96  5682.9   25.05  5747.9   23.23
  5777.9   25.57    5852   24.81    5882   27.96  6136.3      30    6146   30.08
#Mann= 4 , 1 , 0
    3891      .1       0  4972.8    .045       0  5035.9      .1       0
  6136.3      .2       0
Bank Sta=4972.8,5035.9
XS Rating Curve= 0 ,0
Exp/Cntr=0.5,0.3

Type RM Length L Ch R = 1 ,3682.7  ,282.4,282.4,282.4
BEGIN DESCRIPTION:
Upstream Section of Bridge/Culvert/Weir
END DESCRIPTION:
XS GIS Cut Line= 5
      3153304.55     13825307.78      3153311.59     13824906.58
      3153295.66     13824704.76      3153306.28      13824529.5
      3153316.83     13824357.41
#Sta/Elev= 30
  4463.8   24.57  4612.6   22.56  4662.6    22.2  4682.6    21.3  4722.6   20.82
  4742.6   19.29  4762.6   16.55  4772.6   14.78  4812.6   12.53  4822.4   13.84
  4865.4   15.73  4899.1   11.55    4933    8.62  4960.5   12.88  4972.8     4.6
  4974.6    2.59  4974.7   -1.61  5000.8   -7.44  5025.3    -1.5  5025.4     2.3
  5035.9    3.29  5052.6    7.32  5096.2   11.97  5127.5    12.8  5183.6   13.96
    5229   14.53  5235.5   16.77  5315.5   19.04  5395.5   18.13  5415.5    18.4
#Mann= 3 , 1 , 0
  4463.8      .1       0  4972.8    .045       0  5035.9      .1       0
#XS Ineff= 2 , 0
       0  4974.4    21.1  5027.2       0    21.1
Permanent Ineff=
       F       F
Bank Sta=4972.8,5035.9
XS Rating Curve= 0 ,0
Exp/Cntr=0.5,0.3

Type RM Length L Ch R = 2 ,3541.5  ,,,
BEGIN DESCRIPTION:
INTERSTATE ROUTE 610
Structure ID: C02-6
END DESCRIPTION:
Bridge Culvert--1,0,-1,-1, 0
Deck Dist Width WeirC Skew NumUp NumDn MinLoCord MaxHiCord MaxSubmerge Is_Ogee
10,262.4,3,0, 47, 47, , , 0.95, 0, 1,1,,
  4463.8 4463.89    4464 4464.11  4597.7  4612.6  4662.6  4670.4  4670.8  4682.6
  4722.6  4742.6  4754.5  4762.6  4772.6  4812.6  4822.4  4827.8  4865.4  4899.1
    4933  4958.3  4960.5  4972.8  4974.6  4974.7  5000.8  5019.9  5025.3  5025.4
  5035.9  5052.6  5096.2  5127.5  5140.8  5140.9  5183.6    5229  5235.5  5289.1
  5315.5  5349.3  5395.5 5414.89    5415 5415.11  5415.5
   24.55   27.37   30.17   30.17   28.19   27.76   26.31   26.08   26.06   25.77
   24.77   24.28   23.98   23.81   23.61   22.78   22.58   22.47   22.15   21.86
   21.58   21.36   21.37   21.41   21.42   21.42   21.51   21.58    21.6    21.6
   21.63   21.68   21.81   21.91   21.95   21.95   23.15   24.42    24.6    26.1
   27.02    28.2   29.61    30.2    30.2    27.4   18.38
   24.55   24.55   24.55   24.55   22.74   22.54   22.18   21.83   21.81   21.28
    20.8   19.27   17.64   16.53   14.76   12.51   13.82   14.06   15.71   11.53
     8.6   12.52   12.86    4.58    2.57   -1.63   -7.46   -2.83   -1.52    2.28
    3.27     7.3   11.95   12.78   13.06   13.06   13.94   14.51   16.75   18.27
   19.02   18.64   18.11   18.37   18.37   18.37   18.38
  4463.8 4463.89    4464 4464.11  4597.7  4612.6  4662.6  4670.4  4670.8  4682.6
  4722.6  4742.6  4754.5  4762.6  4772.6  4812.6  4822.4  4827.8  4865.4  4899.1
    4933  4958.3  4960.5  4972.8  4974.6  4974.7  5000.8  5019.9  5025.3  5025.4
  5035.9  5052.6  5096.2  5127.5  5140.8  5140.9  5183.6    5229  5235.5  5289.1
  5315.5  5349.3  5395.5 5414.89    5415 5415.11  5415.5
   24.55   27.37   30.17   30.17   28.19   27.76   26.31   26.08   26.06   25.77
   24.77   24.28   23.98   23.81   23.61   22.78   22.58   22.47   22.15   21.86
   21.58   21.36   21.37   21.41   21.42   21.42   21.51   21.58    21.6    21.6
   21.63   21.68   21.81   21.91   21.95   21.95   23.15   24.42    24.6    26.1
   27.02    28.2   29.61    30.2    30.2    27.4   18.38
   24.05   24.05   24.05   24.05   22.24   22.04   21.68   21.33   21.31   20.78
    20.3   18.77   17.14   16.03   14.26   12.01   13.32   13.56   15.21   11.03
     8.1   12.02   12.36    4.08    2.07   -2.13   -7.96   -3.33   -2.02    1.78
    2.77     6.8   11.45   12.28   12.56   12.56   13.44   14.01   16.25   17.77
   18.52   18.14   17.61   17.87   17.87   17.87   17.88
BR Coef= 1 , 0 , 0 ,1.25, 0 ,,,0.8,-1,2,0,
WSPro=,,,, 1 ,,,, 0 ,,,, 0 ,,,,-1 ,-1 ,-1 , 0 , 0 , 0 , 0 , 0
Culvert=2,15,15,262.4,0.015,0.4,1,8,1,-7.99,4991.9,-8.3,4991.9,Culvert #1  , 0 ,10
Culvert Bottom n=0.015
Culvert=2,15,15.5,262.4,0.015,0.4,1,8,1,-7.99,5009.3,-8.3,5009.3,Culvert #2  , 0 ,10
Culvert Bottom n=0.015
BR U #Sta/Elev= 47
  4463.8   24.55 4463.89   24.55    4464   24.55 4464.11   24.55  4597.7   22.74
  4612.6   22.54  4662.6   22.18  4670.4   21.83  4670.8   21.81  4682.6   21.28
  4722.6    20.8  4742.6   19.27  4754.5   17.64  4762.6   16.53  4772.6   14.76
  4812.6   12.51  4822.4   13.82  4827.8   14.06  4865.4   15.71  4899.1   11.53
    4933     8.6  4958.3   12.52  4960.5   12.86  4972.8    4.58  4974.6    2.57
  4974.7   -1.63  5000.8   -7.46  5019.9   -2.83  5025.3   -1.52  5025.4    2.28
  5035.9    3.27  5052.6     7.3  5096.2   11.95  5127.5   12.78  5140.8   13.06
  5140.9   13.06  5183.6   13.94    5229   14.51  5235.5   16.75  5289.1   18.27
  5315.5   19.02  5349.3   18.64  5395.5   18.11 5414.89   18.37    5415   18.37
 5415.11   18.37  5415.5   18.38
BR U #Mann= 3
  4463.8      .1  4972.8    .045  5035.9      .1
BR U Banks=4972.8,5035.9
BR D #Sta/Elev= 47
  4463.8   24.05 4463.89   24.05    4464   24.05 4464.11   24.05  4597.7   22.24
  4612.6   22.04  4662.6   21.68  4670.4   21.33  4670.8   21.31  4682.6   20.78
  4722.6    20.3  4742.6   18.77  4754.5   17.14  4762.6   16.03  4772.6   14.26
  4812.6   12.01  4822.4   13.32  4827.8   13.56  4865.4   15.21  4899.1   11.03
    4933     8.1  4958.3   12.02  4960.5   12.36  4972.8    4.08  4974.6    2.07
  4974.7   -2.13  5000.8   -7.96  5019.9   -3.33  5025.3   -2.02  5025.4    1.78
  5035.9    2.77  5052.6     6.8  5096.2   11.45  5127.5   12.28  5140.8   12.56
  5140.9   12.56  5183.6   13.44    5229   14.01  5235.5   16.25  5289.1   17.77
  5315.5   18.52  5349.3   18.14  5395.5   17.61 5414.89   17.87    5415   17.87
 5415.11   17.87  5415.5   17.88
BR D #Mann= 3
  4463.8      .1  4972.8    .045  5035.9      .1
BR D Banks=4972.8,5035.9
BC Design=,, 0 ,, 0 ,,,,,,
BC HTab HWMax=24.57
BC Use User HTab Curves=0
BC User HTab FreeFlow(D)= 0

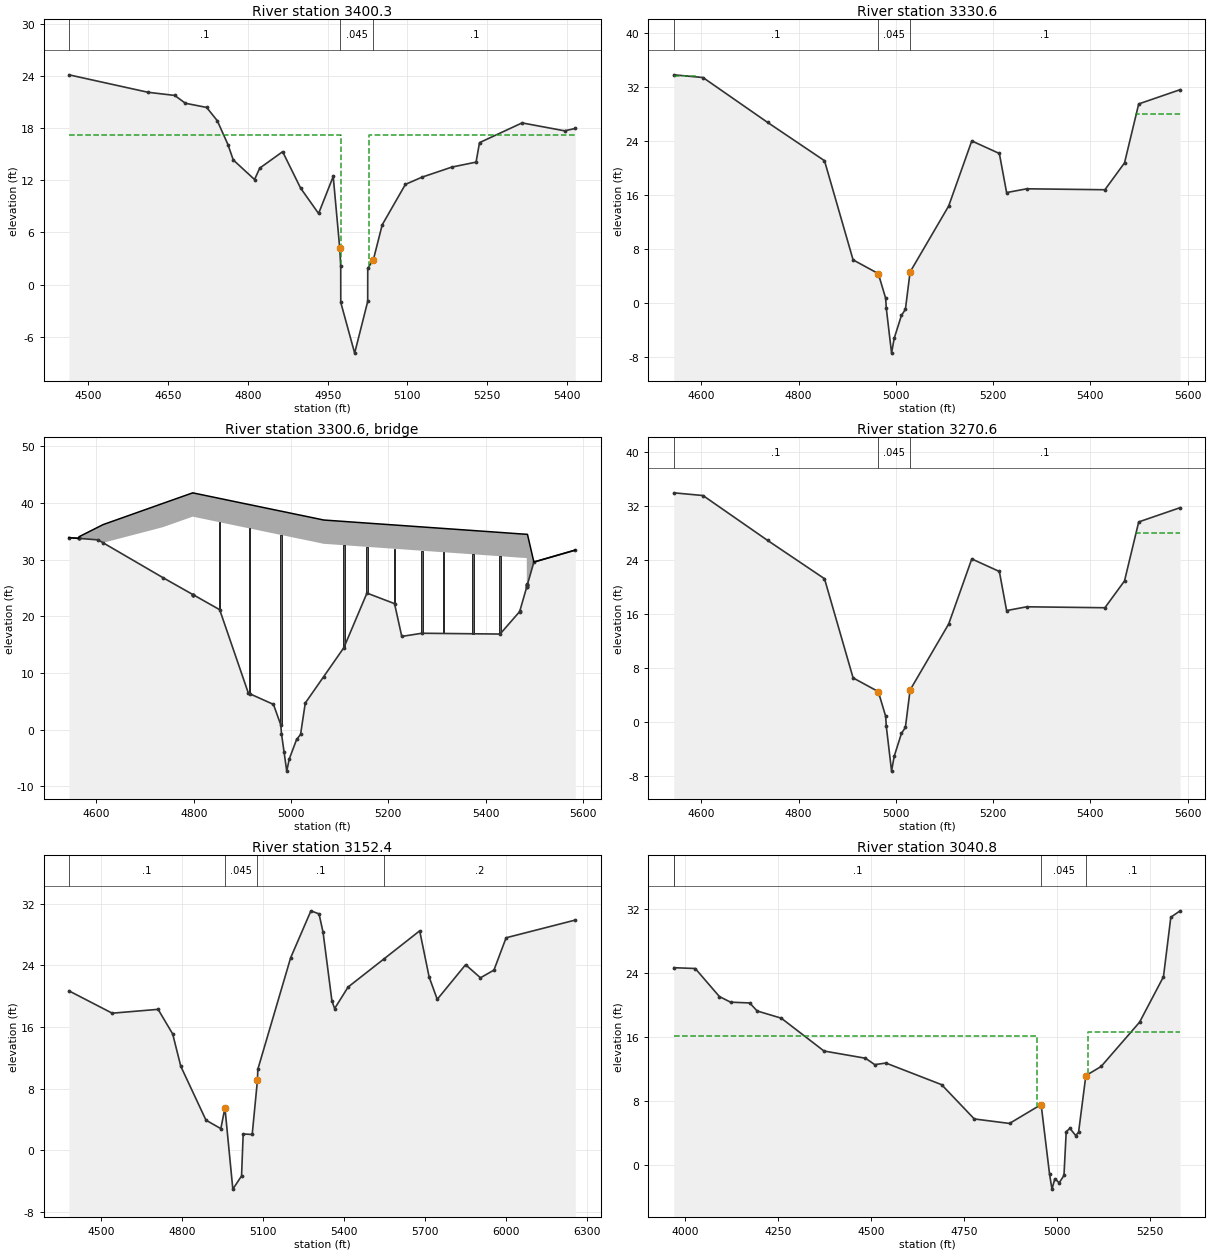
Type RM Length L Ch R = 1 ,3400.3  ,69.7,69.7,69.7
BEGIN DESCRIPTION:
Downstream Section of Bridge/Culvert/Weir
END DESCRIPTION:
XS GIS Cut Line= 5
       3153533.6     13825472.96      3153540.63     13825071.76
       3153524.7     13824869.94      3153535.32     13824694.68
      3153545.88      13824522.6
#Sta/Elev= 30
  4463.8   24.12  4612.6   22.11  4662.6   21.75  4682.6   20.85  4722.6   20.37
  4742.6   18.84  4762.6    16.1  4772.6   14.33  4812.6   12.08  4822.4   13.39
  4865.4   15.28  4899.1    11.1    4933    8.17  4960.5   12.43  4972.8    4.15
  4974.6    2.14  4974.7   -2.06  5000.8   -7.89  5025.3   -1.95  5025.4    1.85
  5035.9    2.84  5052.6    6.87  5096.2   11.52  5127.5   12.35  5183.6   13.51
    5229   14.08  5235.5   16.32  5315.5   18.59  5395.5   17.68  5415.5   17.95
#Mann= 3 , 1 , 0
  4463.8      .1       0  4972.8    .045       0  5035.9      .1       0
#XS Ineff= 2 , 0
       0  4974.4    17.2  5027.2       0    17.2
Permanent Ineff=
       F       F
Bank Sta=4972.8,5035.9
XS Rating Curve= 0 ,0
Exp/Cntr=0.5,0.3

Type RM Length L Ch R = 1 ,3330.6  ,60,60,60
BEGIN DESCRIPTION:
Upstream Section of Bridge/Culvert/Weir
END DESCRIPTION:
XS GIS Cut Line= 5
      3153581.73     13825371.62      3153593.46     13825019.79
      3153605.21     13824855.25      3153546.45     13824731.84
      3153523.85     13824345.27
#Sta/Elev= 22
  4543.5   33.83  4603.5   33.43  4736.4   26.78  4853.3   21.11  4912.1    6.42
  4963.9    4.39    4979     .75  4980.4    -.78  4991.2   -7.39  4996.5   -5.22
  5011.5    -1.8  5019.6    -.92  5029.3    4.63  5108.6    14.4  5156.1   24.04
  5212.8   22.18  5227.7   16.39    5269   16.95  5429.8   16.81  5470.1   20.78
  5499.3   29.52  5584.4   31.63
#Mann= 3 , 1 , 0
  4543.5      .1       0  4963.9    .045       0  5029.3      .1       0
#XS Ineff= 2 , 0
       0  4593.8    33.6  5493.5       0    28.1
Permanent Ineff=
       F       F
Bank Sta=4963.9,5029.3
XS Rating Curve= 0 ,0
Exp/Cntr=0.5,0.3

Type RM Length L Ch R = 3 ,3300.6  ,,,
BEGIN DESCRIPTION:
STATE ROUTE 225 EAST RAMP
Structure ID: C02-4
END DESCRIPTION:
Bridge Culvert--1,0,-1,-1, 0
Deck Dist Width WeirC Skew NumUp NumDn MinLoCord MaxHiCord MaxSubmerge Is_Ogee
10,40,2.6,0, 41, 41, , , 0.95, 0, 1,1,,
  4543.5 4563.41 4563.53  4563.6  4564.6  4603.5  4613.6  4736.4    4798 4798.09
  4798.2 4798.31  4853.3  4912.1  4915.1  4963.9    4979  4980.4  4985.8  4991.2
  4996.5  5011.5  5019.6  5029.3  5067.3  5108.6  5156.1  5212.8  5227.7    5269
  5429.8  5470.1  5470.2 5484.69  5484.8  5485.8 5485.89    5486 5486.11  5499.3
  5584.4
    33.9   33.77   33.77   33.77   34.08   35.76    36.2   39.94   41.81    41.8
    41.8    41.8   40.82   39.77   39.72   38.85   38.58   38.56   38.46   38.37
   38.27      38   37.86   37.69   37.01   36.76   36.47   36.13   36.04   35.79
   34.82   34.57   34.57   34.49   34.49   34.48   34.48   34.48   34.48   29.59
    31.7
    33.9   33.77   33.77   33.77   33.76    33.5   32.99   35.74   37.61    37.6
    37.6    37.6   36.62   35.57   35.52   34.65   34.38   34.36   34.26   34.17
   34.07    33.8   33.66   33.49   32.81   32.56   32.27   31.93   31.84   31.59
   30.62   30.37   30.37   30.29   25.25   25.55   25.58   25.61   25.64   29.59
    31.7
  4543.5 4563.41 4563.53  4563.6  4564.6  4603.5  4613.6  4736.4    4798 4798.09
  4798.2 4798.31  4853.3  4912.1  4915.1  4963.9    4979  4980.4  4985.8  4991.2
  4996.5  5011.5  5019.6  5029.3  5067.3  5108.6  5156.1  5212.8  5227.7    5269
  5429.8  5470.1  5470.2 5484.69  5484.8  5485.8 5485.89    5486 5486.11  5499.3
  5584.4
    33.9   33.77   33.77   33.77   34.08   35.76    36.2   39.94   41.81    41.8
    41.8    41.8   40.82   39.77   39.72   38.85   38.58   38.56   38.46   38.37
   38.27      38   37.86   37.69   37.01   36.76   36.47   36.13   36.04   35.79
   34.82   34.57   34.57   34.49   34.49   34.48   34.48   34.48   34.48   29.59
    31.7
   33.82   33.69   33.69   33.69   33.68   33.42   32.91   35.66   37.53   37.52
   37.52   37.52   36.54   35.49   35.44   34.57    34.3   34.28   34.18   34.09
   33.99   33.72   33.58   33.41   32.73   32.48   32.19   31.85   31.76   31.51
   30.54   30.29   30.29   30.21   25.17   25.47    25.5   25.53   25.56   29.51
   31.62
Pier Skew, UpSta & Num, DnSta & Num=  ,4853.3, 2 ,4853.3, 2 , 0 , 0 , 0 ,,
       3       3
   19.81   37.65
       3       3
   19.73   37.57
Pier Skew, UpSta & Num, DnSta & Num=  ,4915.1, 2 ,4915.1, 2 , 0 , 0 , 0 ,,
       3       3
    5.28   36.55
       3       3
     5.2   36.47
Pier Skew, UpSta & Num, DnSta & Num=  ,4979, 2 ,4979, 2 , 0 , 0 , 0 ,,
       3       3
   -1.77   35.41
       3       3
   -1.85   35.33
Pier Skew, UpSta & Num, DnSta & Num=  ,5108.6, 2 ,5108.6, 2 , 0 , 0 , 0 ,,
       3       3
   13.29   33.57
       3       3
   13.21   33.49
Pier Skew, UpSta & Num, DnSta & Num=  ,5156.1, 2 ,5156.1, 2 , 0 , 0 , 0 ,,
       3       3
   22.81   33.28
       3       3
   22.73    33.2
Pier Skew, UpSta & Num, DnSta & Num=  ,5212.8, 2 ,5212.8, 2 , 0 , 0 , 0 ,,
       3       3
   20.67   32.94
       3       3
   20.59   32.86
Pier Skew, UpSta & Num, DnSta & Num=  ,5269, 2 ,5269, 2 , 0 , 0 , 0 ,,
       3       3
      16    32.6
       3       3
   15.92   32.52
Pier Skew, UpSta & Num, DnSta & Num=  ,5313.9, 2 ,5313.9, 2 , 0 , 0 , 0 ,,
       3       3
   15.98   32.33
       3       3
    15.9   32.25
Pier Skew, UpSta & Num, DnSta & Num=  ,5374.3, 2 ,5374.3, 2 , 0 , 0 , 0 ,,
       3       3
   15.93   31.96
       3       3
   15.85   31.88
Pier Skew, UpSta & Num, DnSta & Num=  ,5429.8, 2 ,5429.8, 2 , 0 , 0 , 0 ,,
       3       3
   15.88   31.63
       3       3
    15.8   31.55
Abutment Skew #Up #Dn= , 2 , 2
  5470.2 5484.89
   20.88   30.29
  5470.2 5484.89
    20.8   30.21
BR Coef= 1 , 1 , 0 ,1.25, 0 ,,,0.8,0,2,0,
WSPro=,,,, 1 ,,,, 0 ,,,, 0 ,,,,-1 ,-1 ,-1 , 0 , 0 , 0 , 0 , 0
BR U #Sta/Elev= 41
  4543.5    33.9 4563.41   33.77 4563.53   33.77  4563.6   33.77  4564.6   33.76
  4603.5    33.5  4613.6   32.99  4736.4   26.85    4798   23.86 4798.09   23.86
  4798.2   23.85 4798.31   23.85  4853.3   21.18  4912.1    6.49  4915.1    6.34
  4963.9    4.46    4979     .82  4980.4    -.71  4985.8      -4  4991.2   -7.32
  4996.5   -5.15  5011.5   -1.73  5019.6    -.85  5029.3     4.7  5067.3    9.38
  5108.6   14.47  5156.1   24.11  5212.8   22.25  5227.7   16.46    5269   17.02
  5429.8   16.88  5470.1   20.85  5470.2   20.88 5484.69   25.22  5484.8   25.25
  5485.8   25.55 5485.89   25.58    5486   25.61 5486.11   25.64  5499.3   29.59
  5584.4    31.7
BR U #Mann= 3
  4543.5      .1  4963.9    .045  5029.3      .1
BR U Banks=4963.9,5029.3
BR D #Sta/Elev= 41
  4543.5   33.82 4563.41   33.69 4563.53   33.69  4563.6   33.69  4564.6   33.68
  4603.5   33.42  4613.6   32.91  4736.4   26.77    4798   23.78 4798.09   23.78
  4798.2   23.77 4798.31   23.77  4853.3    21.1  4912.1    6.41  4915.1    6.26
  4963.9    4.38    4979     .74  4980.4    -.79  4985.8   -4.08  4991.2    -7.4
  4996.5   -5.23  5011.5   -1.81  5019.6    -.93  5029.3    4.62  5067.3     9.3
  5108.6   14.39  5156.1   24.03  5212.8   22.17  5227.7   16.38    5269   16.94
  5429.8    16.8  5470.1   20.77  5470.2    20.8 5484.69   25.14  5484.8   25.17
  5485.8   25.47 5485.89    25.5    5486   25.53 5486.11   25.56  5499.3   29.51
  5584.4   31.62
BR D #Mann= 3
  4543.5      .1  4963.9    .045  5029.3      .1
BR D Banks=4963.9,5029.3
BC Design=,, 0 ,, 0 ,,,,,,
BC HTab HWMax=33.83
BC Use User HTab Curves=0
BC User HTab FreeFlow(D)= 0

Type RM Length L Ch R = 1 ,3270.6  ,118.2,118.2,118.2
BEGIN DESCRIPTION:
Downstream Section of Bridge/Culvert/Weir
END DESCRIPTION:
XS GIS Cut Line= 5
      3153641.34     13825378.46      3153653.06     13825026.63
      3153664.81     13824862.09      3153606.05     13824738.68
      3153583.46     13824352.11
#Sta/Elev= 22
  4543.5      34  4603.5    33.6  4736.4   26.95  4853.3   21.28  4912.1    6.59
  4963.9    4.56    4979     .92  4980.4    -.61  4991.2   -7.22  4996.5   -5.05
  5011.5   -1.63  5019.6    -.75  5029.3     4.8  5108.6   14.57  5156.1   24.21
  5212.8   22.35  5227.7   16.56    5269   17.12  5429.8   16.98  5470.1   20.95
  5499.3   29.69  5584.4    31.8
#Mann= 3 , 1 , 0
  4543.5      .1       0  4963.9    .045       0  5029.3      .1       0
#XS Ineff= 2 , 0
       0  4593.8    33.6  5493.5       0    28.1
Permanent Ineff=
       F       F
Bank Sta=4963.9,5029.3
XS Rating Curve= 0 ,0
Exp/Cntr=0.5,0.3

Type RM Length L Ch R = 1 ,3152.4  ,229,111.6,94
BEGIN DESCRIPTION:
Cross Section 3152.4-Interpolated
END DESCRIPTION:
XS GIS Cut Line= 6
      3153970.43      13825526.7      3153851.11     13825166.98
      3153772.21     13824856.67      3153718.15     13824817.84
      3153658.52     13824729.38      3153582.11     13823730.02
#Sta/Elev= 30
  4380.4    20.7  4540.4    17.8  4710.4    18.3  4764.4    15.1  4794.4    10.9
  4887.7     3.9  4942.7     2.8  4957.9     5.5  4987.1   -5.06  5019.4   -3.35
  5025.4    2.11  5058.8    2.04  5078.3    9.11  5079.6    10.5  5201.2      25
  5276.3    31.1  5306.3    30.7  5321.3    28.3    5354    19.4    5364    18.4
    5414    21.2  5547.7   24.88    5679    28.5    5714    22.5    5744    19.6
    5849    24.1    5904    22.4    5954    23.4    5999    27.6  6255.1    29.9
#Mann= 4 , 1 , 0
  4380.4      .1       0  4957.9    .045       0  5078.3      .1       0
  5547.7      .2       0
Bank Sta=4957.9,5078.3
XS Rating Curve= 0 ,0
Exp/Cntr=0.5,0.3

Type RM Length L Ch R = 1 ,3040.8  ,104.6,104.6,104.6
BEGIN DESCRIPTION:
Upstream Section of Bridge/Culvert/Weir
END DESCRIPTION:
XS GIS Cut Line= 6
      3154745.44     13825460.91      3154244.95     13825105.05
      3153917.36     13824900.06      3153848.08     13824870.37
      3153756.32     13824757.35      3153732.42     13824617.94
#Sta/Elev= 30
  3969.1   24.62  4026.8   24.52  4091.8   21.02  4121.8   20.32  4173.4   20.22
  4193.4   19.22  4258.4   18.32  4373.4   14.22    4485   13.32    4510   12.52
    4540   12.72    4690   10.02    4778    5.74  4872.8    5.18  4957.9    7.54
  4980.6   -1.16  4987.1   -3.02  4994.8   -1.72  5006.5   -2.23  5019.4   -1.31
  5025.4    4.15  5035.4    4.57  5050.9    3.67  5058.7    4.08  5078.3   11.15
  5119.4   12.29  5222.9   17.82  5287.2   23.49    5307   30.92    5332   31.72
#Mann= 4 , 1 , 0
  3969.1      .2       0  3969.1      .1       0  4957.9    .045       0
  5078.3      .1       0
#XS Ineff= 2 , 0
       0    4948    16.1  5084.3       0    16.6
Permanent Ineff=
       F       F
Bank Sta=4957.9,5078.3
XS Rating Curve= 0 ,0
Exp/Cntr=0.5,0.3