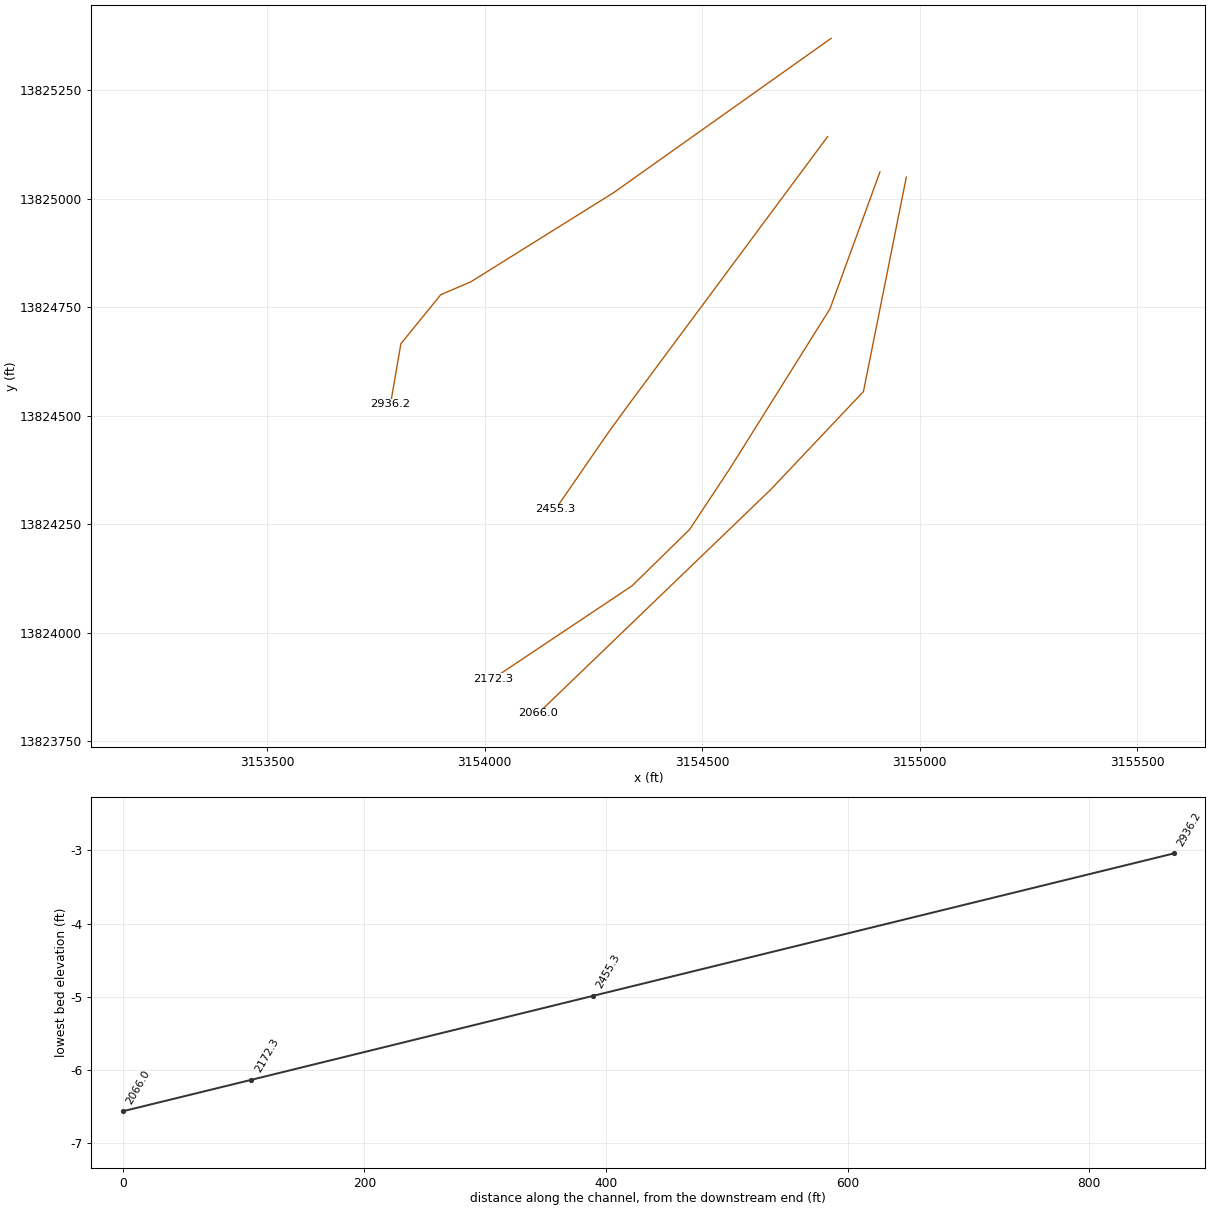
HEC-RAS study C102-00-00.PRJ: C102-00-00

--- C102-00-00.g01 (geometry) --- (continued)

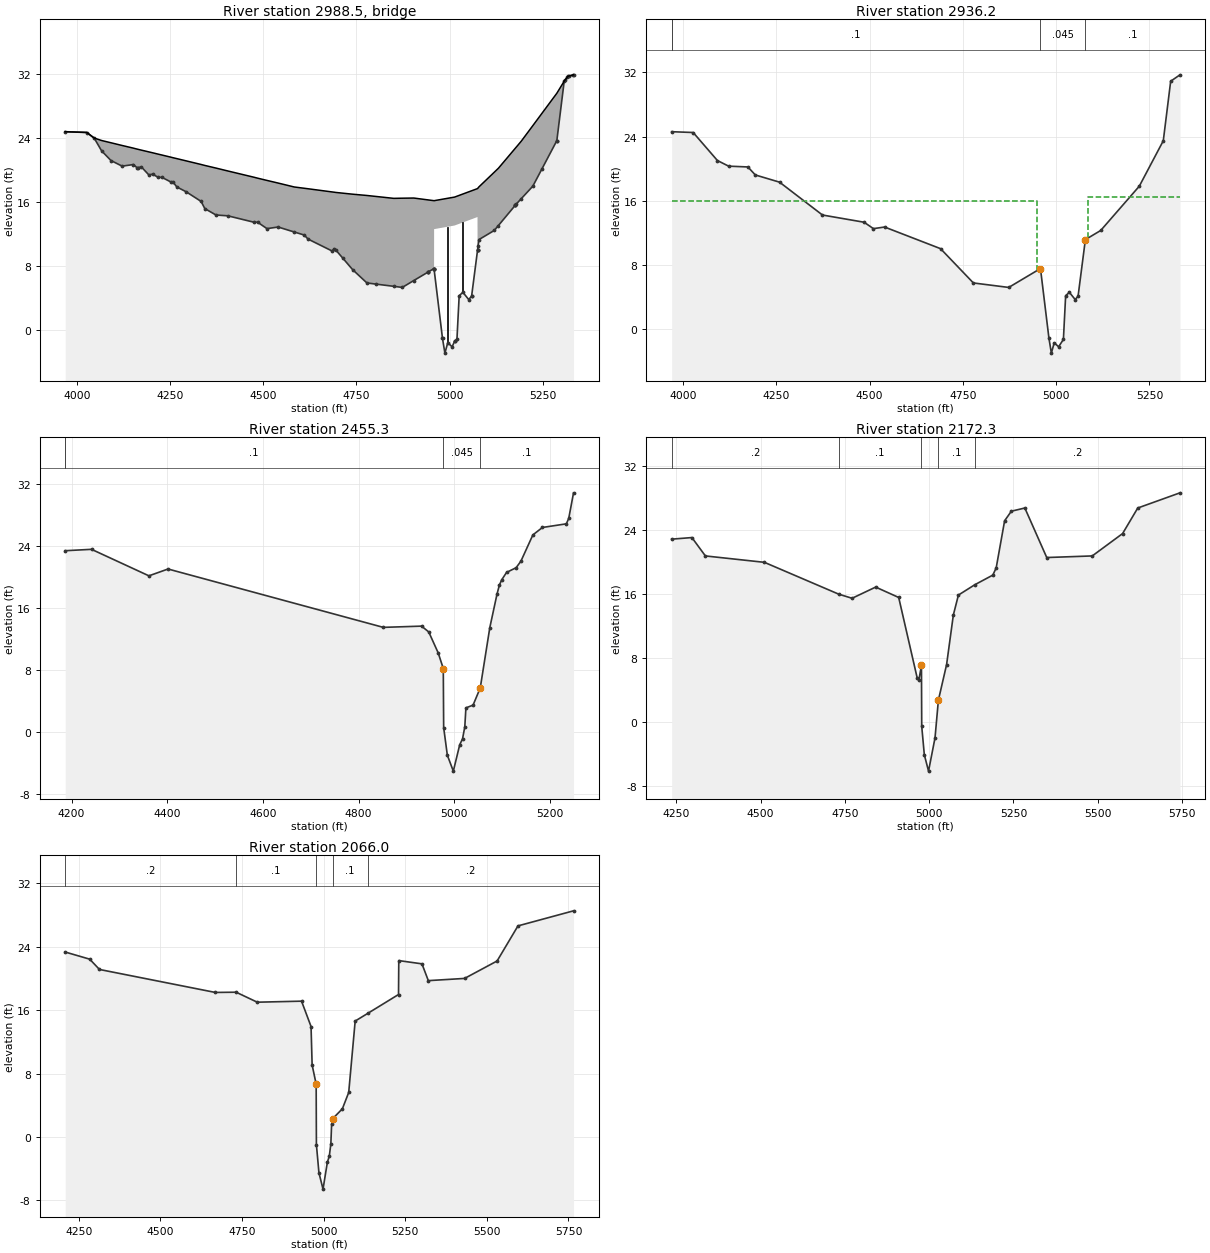
Type RM Length L Ch R = 3 ,2988.5  ,,,
BEGIN DESCRIPTION:
LAWNDALE ROAD ACCESS RAMP
Structure ID: CO2-3
END DESCRIPTION:
Bridge Culvert--1,0,-1,-1, 0
Deck Dist Width WeirC Skew NumUp NumDn MinLoCord MaxHiCord MaxSubmerge Is_Ogee
10,84.6,2.6,0, 52, 52, , , 0.95, 0, 1,1,,
  3969.1  4026.8  4046.8  4066.8  4091.8  4121.8  4151.8  4161.8  4173.4  4193.4
  4203.4  4218.4  4228.4  4253.4  4258.4  4268.4  4293.4  4333.4  4343.4  4373.4
    4405    4475    4485    4510    4540  4583.2    4610    4620    4685    4690
  4694.4  4739.7    4778  4849.9  4872.8  4903.7  4957.9 4958.11  4958.2  5013.1
 5074.59  5074.7  5078.3  5119.4  5130.6 5176.31  5191.7  5222.9  5287.2    5307
    5317    5332
    24.8   24.71   24.01    23.7   23.42   23.08   22.75   22.63    22.5   22.28
   22.17      22   21.89   21.61   21.55   21.44   21.16   20.71   20.59   20.26
    19.9   19.12      19   18.72   18.39    17.9   17.74   17.68   17.28   17.25
   17.22      17   16.84   16.48    16.5   16.52   16.19   16.19   16.19   16.64
    17.7    17.7   17.91   19.74   20.24   22.76   23.61   25.56    29.6   31.11
   31.71    31.9
    24.8    24.7      24    22.4    21.2    20.5    20.7    20.3    20.4    19.4
    19.5    19.1    19.1    18.5    18.5    17.9    17.3    16.1    15.2    14.4
    14.3    13.5    13.5    12.7    12.9   12.28    11.9    11.4     9.9    10.2
   10.04    7.58    5.92     5.5    5.36    6.22    7.72    7.64   12.64   13.09
   14.15   10.03   11.33   12.47   13.09   15.65   16.43      18   23.67    31.1
    31.7    31.9
  3969.1  4026.8  4046.8  4066.8  4091.8  4121.8  4151.8  4161.8  4173.4  4193.4
  4203.4  4218.4  4228.4  4253.4  4258.4  4268.4  4293.4  4333.4  4343.4  4373.4
    4405    4475    4485    4510    4540  4583.2    4610    4620    4685    4690
  4694.4  4739.7    4778  4849.9  4872.8  4903.7  4957.9 4958.11  4958.2  5013.1
 5074.59  5074.7  5078.3  5119.4  5130.6 5176.31  5191.7  5222.9  5287.2    5307
    5317    5332
    24.8   24.71   24.01    23.7   23.42   23.08   22.75   22.63    22.5   22.28
   22.17      22   21.89   21.61   21.55   21.44   21.16   20.71   20.59   20.26
    19.9   19.12      19   18.72   18.39    17.9   17.74   17.68   17.28   17.25
   17.22      17   16.84   16.48    16.5   16.52   16.19   16.19   16.19   16.64
    17.7    17.7   17.91   19.74   20.24   22.76   23.61   25.56    29.6   31.11
   31.71    31.9
   24.64   24.54   23.84   22.24   21.04   20.34   20.54   20.14   20.24   19.24
   19.34   18.94   18.94   18.34   18.34   17.74   17.14   15.94   15.04   14.24
   14.14   13.34   13.34   12.54   12.74   12.12   11.74   11.24    9.74   10.04
    9.88    7.42    5.76    5.34     5.2    6.06    7.56    7.48   12.48   12.93
   13.99    9.87   11.17   12.31   12.93   15.49   16.27   17.84   23.51   30.94
   31.54   31.74
Pier Skew, UpSta & Num, DnSta & Num=  ,4994.8, 2 ,4994.8, 2 , 0 , 0 , 0 ,,
     2.5     2.5
   -2.75   13.95
     2.5     2.5
   -2.91   13.79
Pier Skew, UpSta & Num, DnSta & Num=  ,5035.4, 2 ,5035.4, 2 , 0 , 0 , 0 ,,
     2.5     2.5
    3.68   14.49
     2.5     2.5
    3.52   14.33
Abutment Skew #Up #Dn= , 2 , 2
    4958  4980.7
   12.64   -1.01
    4958  4980.7
   12.48   -1.17
Abutment Skew #Up #Dn= , 2 , 2
  5058.8 5074.79
     4.3   14.15
  5058.8 5074.79
    4.14   13.99
BR Coef= 1 , 1 , 0 ,1.25, 0 ,,,0.8,0,2,0,
WSPro=,,,, 1 ,,,, 0 ,,,, 0 ,,,,-1 ,-1 ,-1 , 0 , 0 , 0 , 0 , 0
BR U #Sta/Elev= 82
  3969.1    24.8  4026.8    24.7  4046.8      24  4066.8    22.4  4091.8    21.2
  4121.8    20.5  4151.8    20.7  4161.8    20.3  4163.4    20.3  4173.4    20.4
  4193.4    19.4  4203.4    19.5  4218.4    19.1  4228.4    19.1  4253.4    18.5
  4258.4    18.5  4268.4    17.9  4293.4    17.3  4333.4    16.1  4343.4    15.2
  4373.4    14.4    4405    14.3    4475    13.5    4485    13.5    4510    12.7
    4540    12.9  4583.2   12.28    4610    11.9    4620    11.4    4685     9.9
    4690    10.2  4694.4   10.04  4712.7    9.05  4739.7    7.58    4778    5.92
  4801.3    5.78  4849.9     5.5  4872.8    5.36  4903.7    6.22 4941.09    7.25
  4941.2    7.26 4941.31    7.26  4957.9    7.72    4958    7.68 4958.11    7.64
  4958.2    7.61  4980.6    -.98  4980.7   -1.01  4987.1   -2.84  4994.8   -1.54
  5006.5   -2.05  5013.1   -1.36  5013.4   -1.33  5019.4   -1.13  5025.4    4.33
  5035.4    4.75  5050.9    3.85  5058.7    4.26  5058.8     4.3 5074.59    9.99
  5074.7   10.03  5074.8   10.07    5076    10.5  5078.3   11.33  5119.4   12.47
  5130.6   13.09 5176.09   15.63  5176.2   15.64 5176.31   15.65  5178.9   15.79
  5191.7   16.43  5222.9      18  5246.7    20.1  5287.1   23.67  5287.2   23.67
    5307    31.1  5309.8   31.27  5315.6   31.62    5317    31.7  5320.6   31.75
  5331.6   31.89    5332    31.9
BR U #Mann= 4
  3969.1      .2  3969.1      .1  4957.9    .045  5078.3      .1
BR U Banks=4957.9,5078.3
BR D #Sta/Elev= 82
  3969.1   24.64  4026.8   24.54  4046.8   23.84  4066.8   22.24  4091.8   21.04
  4121.8   20.34  4151.8   20.54  4161.8   20.14  4163.4   20.14  4173.4   20.24
  4193.4   19.24  4203.4   19.34  4218.4   18.94  4228.4   18.94  4253.4   18.34
  4258.4   18.34  4268.4   17.74  4293.4   17.14  4333.4   15.94  4343.4   15.04
  4373.4   14.24    4405   14.14    4475   13.34    4485   13.34    4510   12.54
    4540   12.74  4583.2   12.12    4610   11.74    4620   11.24    4685    9.74
    4690   10.04  4694.4    9.88  4712.7    8.89  4739.7    7.42    4778    5.76
  4801.3    5.62  4849.9    5.34  4872.8     5.2  4903.7    6.06 4941.09    7.09
  4941.2     7.1 4941.31     7.1  4957.9    7.56    4958    7.52 4958.11    7.48
  4958.2    7.45  4980.6   -1.14  4980.7   -1.17  4987.1      -3  4994.8    -1.7
  5006.5   -2.21  5013.1   -1.52  5013.4   -1.49  5019.4   -1.29  5025.4    4.17
  5035.4    4.59  5050.9    3.69  5058.7     4.1  5058.8    4.14 5074.59    9.83
  5074.7    9.87  5074.8    9.91    5076   10.34  5078.3   11.17  5119.4   12.31
  5130.6   12.93 5176.09   15.47  5176.2   15.48 5176.31   15.49  5178.9   15.63
  5191.7   16.27  5222.9   17.84  5246.7   19.94  5287.1   23.51  5287.2   23.51
    5307   30.94  5309.8   31.11  5315.6   31.46    5317   31.54  5320.6   31.59
  5331.6   31.73    5332   31.74
BR D #Mann= 4
  3969.1      .2  3969.1      .1  4957.9    .045  5078.3      .1
BR D Banks=4957.9,5078.3
BC Design=,, 0 ,, 0 ,,,,,,
BC HTab HWMax=31.72
BC Use User HTab Curves=0
BC User HTab FreeFlow(D)= 0

Type RM Length L Ch R = 1 ,2936.2  ,480.9,480.9,480.9
BEGIN DESCRIPTION:
Downstream Section of Bridge/Culvert/Weir
END DESCRIPTION:
XS GIS Cut Line= 6
      3154796.66     13825369.71      3154296.17     13825013.85
      3153968.58     13824808.86       3153899.3     13824779.17
      3153807.54     13824666.15      3153783.63     13824526.73
#Sta/Elev= 30
  3969.1    24.6  4026.8    24.5  4091.8      21  4121.8    20.3  4173.4    20.2
  4193.4    19.2  4258.4    18.3  4373.4    14.2    4485    13.3    4510    12.5
    4540    12.7    4690      10    4778    5.72  4872.8    5.16  4957.9    7.52
  4980.6   -1.18  4987.1   -3.04  4994.8   -1.74  5006.5   -2.25  5019.4   -1.33
  5025.4    4.13  5035.4    4.55  5050.9    3.65  5058.7    4.06  5078.3   11.13
  5119.4   12.27  5222.9    17.8  5287.2   23.47    5307    30.9    5332    31.7
#Mann= 4 , 1 , 0
  3969.1      .2       0  3969.1      .1       0  4957.9    .045       0
  5078.3      .1       0
#XS Ineff= 2 , 0
       0    4948    15.9  5084.8       0    16.4
Permanent Ineff=
       F       F
Bank Sta=4957.9,5078.3
XS Rating Curve= 0 ,0
Exp/Cntr=0.5,0.3

Type RM Length L Ch R = 1 ,2455.3  ,282.7,283,290.2
BEGIN DESCRIPTION:
Cross Section 2455.3-Interpolated
END DESCRIPTION:
XS GIS Cut Line= 4
      3154788.52      13825143.2      3154330.32     13824524.62
       3154284.5     13824461.62       3154162.7     13824284.45
#Sta/Elev= 30
  4186.7   23.45  4241.7   23.63  4361.7   20.21  4401.7   21.09  4851.7   13.56
  4931.7   13.72  4946.7   12.97  4966.5   10.26  4977.1    8.25  4977.9     .63
  4985.6   -2.94  4998.1   -4.99  5011.4    -1.6  5017.4    -.81  5022.1     .73
  5024.4    3.17  5039.4    3.53  5054.4    5.75  5074.4   13.54  5089.4   17.84
  5094.4   19.02  5099.4   19.71  5109.4   20.65  5129.4   21.26  5139.4    22.1
  5164.4   25.49  5184.4   26.45  5234.4   26.92  5239.4   27.63  5249.4   30.92
#Mann= 4 , 1 , 0
  4186.7      .2       0  4186.7      .1       0  4977.1    .045       0
  5054.4      .1       0
Bank Sta=4977.1,5054.4
XS Rating Curve= 0 ,0
Exp/Cntr=0.3,0.1

Type RM Length L Ch R = 1 ,2172.3  ,124.6,106.3,101.4
BEGIN DESCRIPTION:
Cross Section 2172.3-Interpolated
END DESCRIPTION:
XS GIS Cut Line= 6
      3154908.91     13825061.86      3154794.19     13824746.92
       3154566.1      13824381.9      3154471.38     13824238.25
      3154339.32     13824108.63      3154019.15     13823894.33
#Sta/Elev= 30
  4236.1    22.9  4296.1    23.1  4336.1    20.8  4511.1      20  4731.9   16.01
  4771.3    15.5  4841.3    16.9  4909.6    15.6  4964.6     5.5  4969.6     5.3
  4977.1     7.1  4977.9    -.52  4985.6   -4.09  4998.1   -6.14  5017.4   -1.96
  5027.3    2.73  5051.7     7.2  5071.7    13.4  5086.7    15.9  5135.6    17.2
  5188.8    18.4  5198.8    19.3  5223.8    25.2  5243.8    26.4  5283.8    26.8
  5348.8    20.6  5483.8    20.8  5573.8    23.6  5618.8    26.8  5744.1    28.7
#Mann= 5 , 1 , 0
  4236.1      .2       0  4731.9      .1       0  4977.1    .045       0
  5027.3      .1       0  5135.6      .2       0
Bank Sta=4977.1,5027.3
XS Rating Curve= 0 ,0
Exp/Cntr=0.5,0.3

Type RM Length L Ch R = 1 ,2066.0  ,26.2,26.2,26.2
BEGIN DESCRIPTION:
Upstream Section of Bridge/Culvert/Weir
END DESCRIPTION:
XS GIS Cut Line= 5
      3154969.59     13825050.26      3154871.01     13824556.03
      3154692.33     13824366.65      3154657.91     13824330.19
       3154123.1     13823814.51
#Sta/Elev= 30
  4208.2   23.35  4283.2   22.45  4313.2   21.15  4668.2   18.25  4731.9   18.28
  4796.6   17.02  4932.3   17.15  4961.4   13.95  4964.7     9.1  4977.1    6.67
  4977.8    -.95  4985.6   -4.52  4998.1   -6.57  5011.4   -3.18  5017.4   -2.39
  5022.1    -.85  5024.4    1.59  5027.3     2.3  5057.4    3.57  5076.8    5.63
  5096.6   14.64  5135.6   15.62  5229.4   17.99  5230.2   22.27  5301.2   21.86
  5320.7   19.74  5431.8   20.02  5531.4   22.22  5595.4   26.65  5765.6   28.55
#Mann= 5 , 1 , 0
  4208.2      .2       0  4731.9      .1       0  4977.1    .045       0
  5027.3      .1       0  5135.6      .2       0
#XS Ineff= 2 , 0
       0  4961.6    13.4  5093.6       0    13.2
Permanent Ineff=
       F       F
Bank Sta=4977.1,5027.3
XS Rating Curve= 0 ,0
Exp/Cntr=0.5,0.3