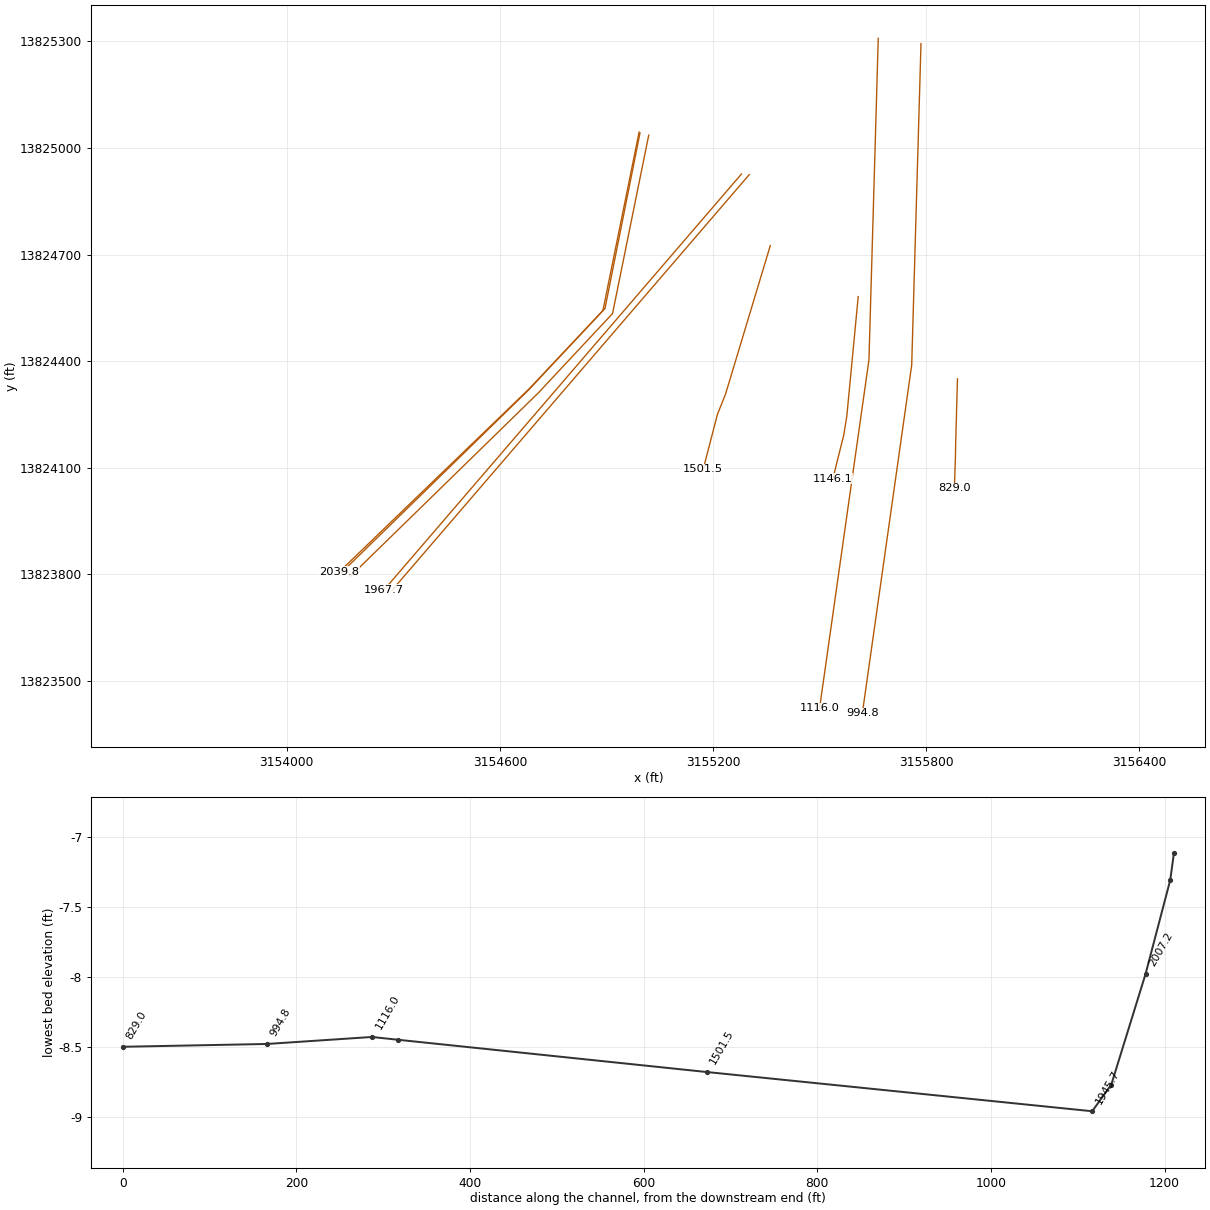
HEC-RAS study C102-00-00.PRJ: C102-00-00

--- C102-00-00.g01 (geometry) --- (continued)

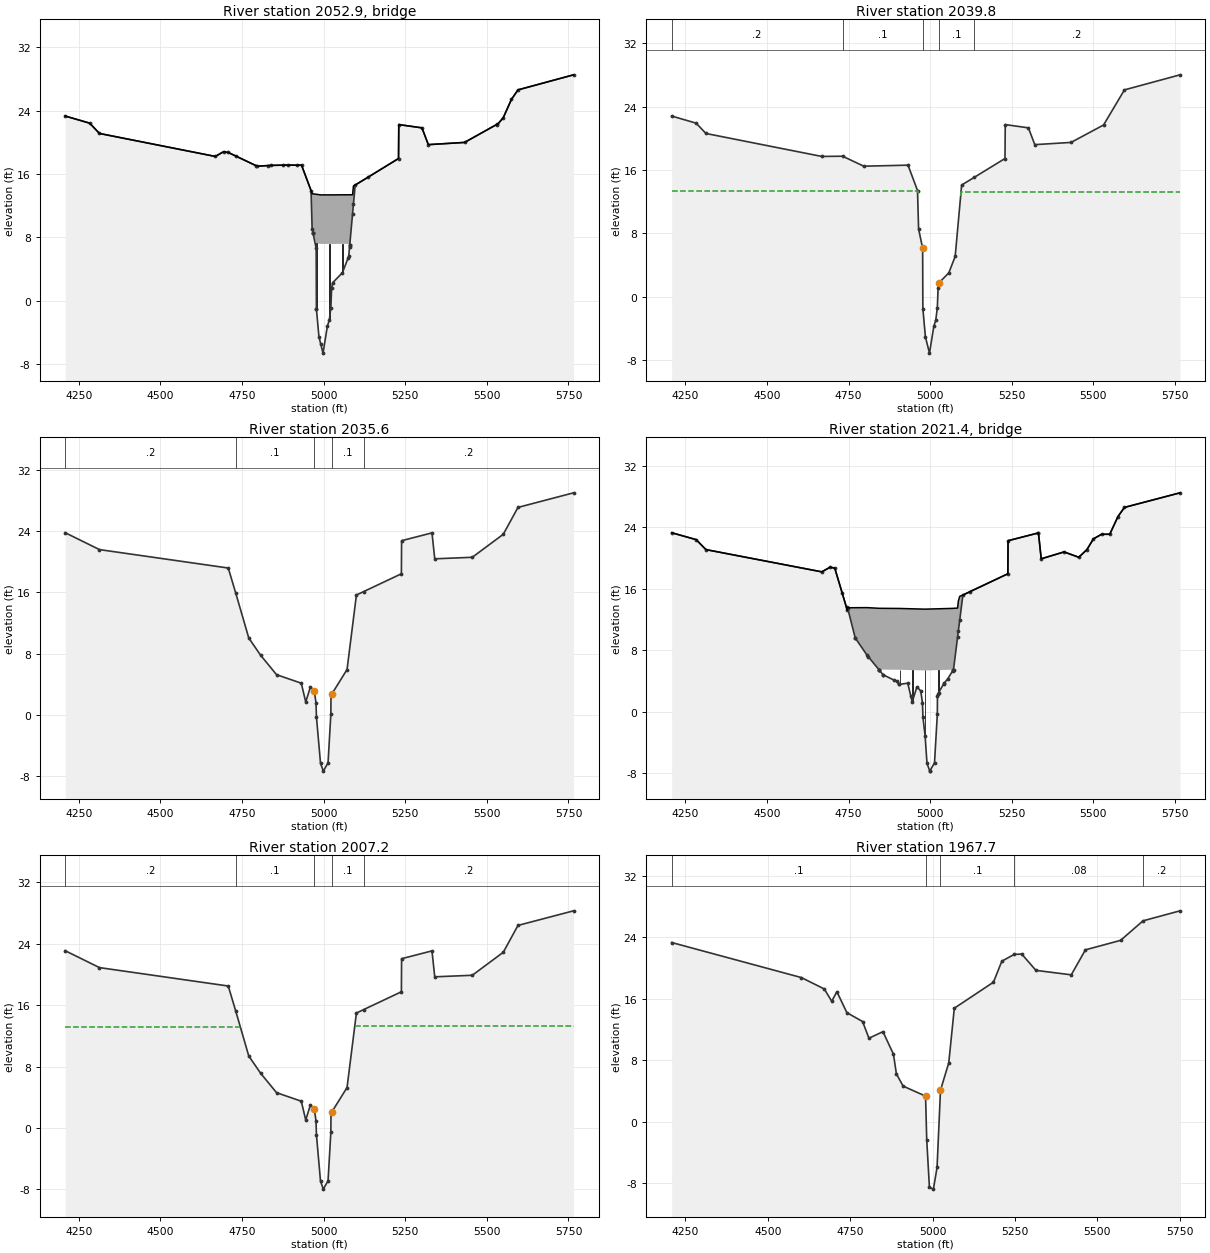
Type RM Length L Ch R = 3 ,2052.9  ,,,
BEGIN DESCRIPTION:
RECTANGULAR PIPELINE
Structure ID: C02-2B
END DESCRIPTION:
Bridge Culvert--1,0,-1,-1, 0
Deck Dist Width WeirC Skew NumUp NumDn MinLoCord MaxHiCord MaxSubmerge Is_Ogee
10,6.2,2.6,0, 52, 52, , , 0.95, 0, 1,1,,
  4208.2  4283.2  4313.2  4668.2  4693.2  4707.8  4731.9  4792.3  4796.6  4829.8
  4838.5  4874.8  4891.8  4919.8  4932.3  4961.4  4964.7  4967.1 4967.21  4967.3
  4977.1  4977.8  4977.9  4985.6  4990.8  4998.1  5011.4  5017.4  5022.1  5024.4
  5027.3  5057.4  5075.3  5076.8  5079.3 5079.99  5080.1  5088.7  5091.3  5096.6
  5135.6  5229.4  5230.2  5301.2  5320.7  5431.8  5531.3  5531.4  5550.4  5575.4
  5595.4  5765.6
   23.31   22.41   21.11   18.21   18.81   18.71   18.24   17.06   16.98   17.06
   17.08   17.11   17.12   17.11   17.11   13.91   13.49   13.49   13.49   13.49
   13.44   13.43   13.43   13.39   13.36   13.36   13.36   13.36   13.36   13.36
   13.36   13.37   13.37   13.37   13.37   13.37   13.37   13.38   14.49    14.6
   15.58   17.95   22.23   21.82    19.7   19.98   22.27   22.18   23.11   25.41
   26.61   28.51
   23.31   22.41   21.11   18.21   18.81   18.71   18.24   17.06   16.98   17.06
   17.08   17.11   17.12   17.11   17.11   13.91    9.06    8.59    8.57    8.55
    7.25    7.24    7.24     7.2    7.17    7.17    7.17    7.17    7.17    7.17
    7.17    7.18    7.18    7.18    7.18    7.18    7.09   11.01   12.19    14.6
   15.58   17.95   22.23   21.82    19.7   19.98   22.27   22.18   23.11   25.41
   26.61   28.51
  4208.2  4283.2  4313.2  4668.2  4693.2  4707.8  4731.9  4792.3  4796.6  4829.8
  4838.5  4874.8  4891.8  4919.8  4932.3  4961.4  4964.7  4967.1 4967.21  4967.3
  4977.1  4977.8  4977.9  4985.6  4990.8  4998.1  5011.4  5017.4  5022.1  5024.4
  5027.3  5057.4  5075.3  5076.8  5079.3 5079.99  5080.1  5088.7  5091.3  5096.6
  5135.6  5229.4  5230.2  5301.2  5320.7  5431.8  5531.3  5531.4  5550.4  5575.4
  5595.4  5765.6
    23.3    22.4    21.1    18.2    18.8    18.7   18.23   17.06   16.98   17.06
   17.08   17.11   17.12   17.11   17.11   13.91   13.49   13.49   13.49   13.49
   13.44   13.43   13.43   13.39   13.36   13.36   13.36   13.36   13.36   13.36
   13.36   13.37   13.37   13.37   13.37   13.37   13.37   13.38   14.49   14.59
   15.57   17.94   22.22   21.81   19.69   19.97   22.26   22.17    23.1    25.4
    26.6    28.5
   23.24   22.34   21.04   18.14   18.74   18.64   18.17   16.99   16.91   16.99
   17.01   17.04   17.05   17.04   17.04   13.84    8.99    8.52     8.5    8.48
    7.18    7.17    7.17    7.13     7.1     7.1     7.1     7.1     7.1     7.1
     7.1    7.11    7.11    7.11    7.11    7.11    7.02   10.94   12.12   14.53
   15.51   17.88   22.16   21.75   19.63   19.91    22.2   22.11   23.04   25.34
   26.54   28.44
Pier Skew, UpSta & Num, DnSta & Num=  ,4977.9, 2 ,4977.9, 2 , 0 , 0 , 0 ,,
     1.5     1.5
   -2.38    8.25
     1.5     1.5
   -2.45    8.18
Pier Skew, UpSta & Num, DnSta & Num=  ,5017.4, 2 ,5017.4, 2 , 0 , 0 , 0 ,,
     1.2     1.2
   -3.51    8.17
     1.2     1.2
   -3.58     8.1
Pier Skew, UpSta & Num, DnSta & Num=  ,5057.4, 2 ,5057.4, 2 , 0 , 0 , 0 ,,
     1.2     1.2
     2.5    8.18
     1.2     1.2
    2.43    8.11
Abutment Skew #Up #Dn= , 2 , 2
  4967.1  4977.9
    8.55   -1.04
  4967.1  4977.9
    8.48   -1.11
BR Coef= 1 , 1 , 0 ,1.25, 0 ,,,0.8,0,2,0,
WSPro=,,,, 1 ,,,, 0 ,,,, 0 ,,,,-1 ,-1 ,-1 , 0 , 0 , 0 , 0 , 0
BR U #Sta/Elev= 52
  4208.2   23.31  4283.2   22.41  4313.2   21.11  4668.2   18.21  4693.2   18.81
  4707.8   18.71  4731.9   18.24  4792.3   17.06  4796.6   16.98  4829.8   17.06
  4838.5   17.08  4874.8   17.11  4891.8   17.12  4919.8   17.11  4932.3   17.11
  4961.4   13.91  4964.7    9.06  4967.1    8.59 4967.21    8.57  4967.3    8.55
  4977.1    6.63  4977.8    -.99  4977.9   -1.04  4985.6   -4.56  4990.8   -5.41
  4998.1   -6.61  5011.4   -3.22  5017.4   -2.43  5022.1    -.89  5024.4    1.55
  5027.3    2.26  5057.4    3.53  5075.3    5.43  5076.8    5.59  5079.3    6.73
 5079.99    7.04  5080.1    7.09  5088.7   11.01  5091.3   12.19  5096.6    14.6
  5135.6   15.58  5229.4   17.95  5230.2   22.23  5301.2   21.82  5320.7    19.7
  5431.8   19.98  5531.3   22.27  5531.4   22.18  5550.4   23.11  5575.4   25.41
  5595.4   26.61  5765.6   28.51
BR U #Mann= 5
  4208.2      .2  4731.9      .1  4977.1    .045  5027.3      .1  5135.6      .2
BR U Banks=4977.1,5027.3
BR D #Sta/Elev= 52
  4208.2   23.24  4283.2   22.34  4313.2   21.04  4668.2   18.14  4693.2   18.74
  4707.8   18.64  4731.9   18.17  4792.3   16.99  4796.6   16.91  4829.8   16.99
  4838.5   17.01  4874.8   17.04  4891.8   17.05  4919.8   17.04  4932.3   17.04
  4961.4   13.84  4964.7    8.99  4967.1    8.52 4967.21     8.5  4967.3    8.48
  4977.1    6.56  4977.8   -1.06  4977.9   -1.11  4985.6   -4.63  4990.8   -5.48
  4998.1   -6.68  5011.4   -3.29  5017.4    -2.5  5022.1    -.96  5024.4    1.48
  5027.3    2.19  5057.4    3.46  5075.3    5.36  5076.8    5.52  5079.3    6.66
 5079.99    6.97  5080.1    7.02  5088.7   10.94  5091.3   12.12  5096.6   14.53
  5135.6   15.51  5229.4   17.88  5230.2   22.16  5301.2   21.75  5320.7   19.63
  5431.8   19.91  5531.3    22.2  5531.4   22.11  5550.4   23.04  5575.4   25.34
  5595.4   26.54  5765.6   28.44
BR D #Mann= 5
  4208.2      .2  4731.9      .1  4977.1    .045  5027.3      .1  5135.6      .2
BR D Banks=4977.1,5027.3
BC Design=,, 0 ,, 0 ,,,,,,
BC HTab HWMax=28.55
BC Use User HTab Curves=0
BC User HTab FreeFlow(D)= 0

Type RM Length L Ch R = 1 ,2039.8  ,4.2,4.2,4.2
BEGIN DESCRIPTION:
Downstream Section of Bridge/Culvert/Weir
END DESCRIPTION:
XS GIS Cut Line= 5
      3154994.58     13825042.39      3154896.01     13824548.17
      3154717.33     13824358.79      3154682.91     13824322.33
       3154148.1     13823806.65
#Sta/Elev= 30
  4208.2    22.8  4283.2    21.9  4313.2    20.6  4668.2    17.7  4731.9   17.73
  4796.6   16.47  4932.3    16.6  4961.4    13.4  4964.7    8.55  4977.1    6.12
  4977.8    -1.5  4985.6   -5.07  4998.1   -7.12  5011.4   -3.73  5017.4   -2.94
  5022.1    -1.4  5024.4    1.04  5027.3    1.75  5057.4    3.02  5076.8    5.08
  5096.6   14.09  5135.6   15.07  5229.4   17.44  5230.2   21.72  5301.2   21.31
  5320.7   19.19  5431.8   19.47  5531.4   21.67  5595.4    26.1  5765.6      28
#Mann= 5 , 1 , 0
  4208.2      .2       0  4731.9      .1       0  4977.1    .045       0
  5027.3      .1       0  5135.6      .2       0
#XS Ineff= 2 , 0
       0  4961.6    13.4  5093.6       0    13.2
Permanent Ineff=
       F       F
Bank Sta=4977.1,5027.3
XS Rating Curve= 0 ,0
Exp/Cntr=0.5,0.3

Type RM Length L Ch R = 1 ,2035.6  ,28.4,28.4,28.4
BEGIN DESCRIPTION:
Upstream Section of Bridge/Culvert/Weir
END DESCRIPTION:
XS GIS Cut Line= 5
      3154992.08     13825044.52      3154890.24     13824542.39
      3154721.84     13824362.44      3154682.69     13824320.39
       3154152.5     13823802.88
#Sta/Elev= 30
  4208.2   23.76  4313.2   21.56  4707.8   19.16  4730.9   15.86  4770.6   10.04
  4806.8     7.8  4855.7    5.26  4931.5    4.15  4945.1     1.7  4959.5    3.66
  4971.2    3.15  4976.6    1.59  4977.9    -.22  4990.4   -6.27    4999   -7.31
  5013.5   -6.22  5022.1     .11  5022.5    2.43  5024.3    2.69  5071.7    5.93
  5100.4   15.64  5123.1    16.1  5238.2   18.41  5238.8   22.72  5331.9   23.74
  5340.4   20.36  5455.4   20.56  5550.4   23.56  5595.4   27.06  5765.6   28.96
#Mann= 5 , 1 , 0
  4208.2      .2       0  4730.9      .1       0  4971.2    .045       0
  5024.3      .1       0  5123.1      .2       0
#XS Ineff= 2 , 0
       0    4747    13.2  5095.3       0    13.3
Permanent Ineff=
       F       F
Bank Sta=4971.2,5024.3
XS Rating Curve= 0 ,0
Exp/Cntr=0.5,0.3

Type RM Length L Ch R = 3 ,2021.4  ,,,
BEGIN DESCRIPTION:
RECTANGULAR PIPELINE
Structure ID: C02-2A
END DESCRIPTION:
Bridge Culvert--1,0,-1,-1, 0
Deck Dist Width WeirC Skew NumUp NumDn MinLoCord MaxHiCord MaxSubmerge Is_Ogee
10,8.4,2.6,0, 36, 35, , , 0.95, 0, 1,1,,
  4208.2  4283.2  4313.2  4668.2  4693.2  4707.8  4746.4  4746.7  4747.1  4770.6
  4806.8 4844.11  4844.2  4906.1  4984.7  5069.3 5069.99  5070.1  5071.7  5084.2
  5086.5  5090.7  5100.4  5238.2  5238.8  5331.9  5340.4  5410.4  5455.4  5480.4
  5500.4  5525.4  5550.4  5575.4  5595.4  5765.6
   23.31   22.41   21.11   18.21   18.81   18.71    13.2   13.59   13.53   13.54
   13.55   13.46   13.46   13.44   13.35   13.45   13.45   13.45   13.46   13.49
    14.4   15.02   15.19   17.96   22.27   23.29   19.91   20.81   20.11   21.11
   22.51   23.11   23.11   25.41   26.61   28.51
   23.31   22.41   21.11   18.21   18.81   18.71    13.2   13.59   13.52    9.59
    7.35    5.41    5.47    5.45    5.36    5.46    5.46    5.37    5.48    9.71
   10.49   11.91   15.19   17.96   22.27   23.29   19.91   20.81   20.11   21.11
   22.51   23.11   23.11   25.41   26.61   28.51
  4208.2  4283.2  4313.2  4668.2  4693.2  4707.8  4746.4  4746.7  4770.6  4806.8
 4844.11  4844.2  4906.1  4984.7  5069.3 5069.99  5070.1  5071.7  5084.2  5086.5
  5090.7  5100.4  5238.2  5238.8  5331.9  5340.4  5410.4  5455.4  5480.4  5500.4
  5525.4  5550.4  5575.4  5595.4  5765.6
    23.3    22.4    21.1    18.2    18.8    18.7   13.19   13.58   13.54   13.55
   13.46   13.46   13.44   13.35   13.45   13.45   13.45   13.46   13.49    14.4
   15.02   15.18   17.95   22.26   23.28    19.9    20.8    20.1    21.1    22.5
    23.1    23.1    25.4    26.6    28.5
   23.29   22.39   21.09   18.19   18.79   18.69   13.18   13.57    9.57    7.33
    5.39    5.45    5.43    5.34    5.44    5.44    5.35    5.46    9.69   10.47
   11.89   15.17   17.94   22.25   23.27   19.89   20.79   20.09   21.09   22.49
   23.09   23.09   25.39   26.59   28.49
Pier Skew, UpSta & Num, DnSta & Num=  ,4907.9, 2 ,4907.9, 2 , 0 , 0 , 0 ,,
     2.5     2.5
    2.55    6.45
     2.5     2.5
    2.53    6.43
Pier Skew, UpSta & Num, DnSta & Num=  ,4945.1, 2 ,4945.1, 2 , 0 , 0 , 0 ,,
     2.5     2.5
     .42    6.38
     2.5     2.5
      .4    6.36
Pier Skew, UpSta & Num, DnSta & Num=  ,4984.7, 2 ,4984.7, 2 , 0 , 0 , 0 ,,
     1.2     1.2
   -4.54    6.36
     1.2     1.2
   -4.56    6.34
Pier Skew, UpSta & Num, DnSta & Num=  ,5025.7, 2 ,5025.7, 2 , 0 , 0 , 0 ,,
     2.5     2.5
    1.26    6.38
     2.5     2.5
    1.24    6.36
BR Coef= 1 , 1 , 0 ,1.25, 0 ,,,0.8,0,2,0,
WSPro=,,,, 1 ,,,, 0 ,,,, 0 ,,,,-1 ,-1 ,-1 , 0 , 0 , 0 , 0 , 0
BR U #Sta/Elev= 65
  4208.2   23.31  4283.2   22.41  4313.2   21.11  4668.2   18.21  4693.2   18.81
  4707.8   18.71  4730.9   15.41  4746.4    13.2  4746.7   13.59  4747.1   13.52
  4770.6    9.59  4771.1    9.56  4806.8    7.35  4810.6    7.15 4844.11    5.41
  4844.2    5.41  4844.8    5.38  4855.7    4.81  4856.6    4.79    4888    4.13
  4897.1    3.94  4904.9    3.54  4906.1    3.55  4931.5     3.7    4941    1.99
  4945.1    1.25  4959.5    3.21  4971.2     2.7  4976.6    1.14  4977.9    -.67
  4984.7   -3.17  4990.4   -6.72  4998.9   -7.75    4999   -7.76  5013.5   -6.67
  5022.1    -.34  5022.5    1.98  5024.3    2.24  5025.7    2.44  5042.1    3.65
  5042.7    3.68  5053.7    4.25  5069.3    5.32 5069.99    5.36  5070.1    5.37
  5071.7    5.48  5084.2    9.71  5086.5   10.49  5090.7   11.91  5100.4   15.19
  5123.1   15.65  5238.2   17.96  5238.8   22.27  5331.8   23.28  5331.9   23.29
  5340.4   19.91  5410.4   20.81  5455.4   20.11  5480.4   21.11  5500.4   22.51
  5525.4   23.11  5550.4   23.11  5575.4   25.41  5595.4   26.61  5765.6   28.51
BR U #Mann= 5
  4208.2      .2  4730.9      .1  4971.2    .045  5024.3      .1  5123.1      .2
BR U Banks=4971.2,5024.3
BR D #Sta/Elev= 65
  4208.2   23.29  4283.2   22.39  4313.2   21.09  4668.2   18.19  4693.2   18.79
  4707.8   18.69  4730.9   15.39  4746.4   13.18  4746.7   13.57  4747.1    13.5
  4770.6    9.57  4771.1    9.54  4806.8    7.33  4810.6    7.13 4844.11    5.39
  4844.2    5.39  4844.8    5.36  4855.7    4.79  4856.6    4.77    4888    4.11
  4897.1    3.92  4904.9    3.52  4906.1    3.53  4931.5    3.68    4941    1.97
  4945.1    1.23  4959.5    3.19  4971.2    2.68  4976.6    1.12  4977.9    -.69
  4984.7   -3.19  4990.4   -6.74  4998.9   -7.77    4999   -7.78  5013.5   -6.69
  5022.1    -.36  5022.5    1.96  5024.3    2.22  5025.7    2.42  5042.1    3.63
  5042.7    3.66  5053.7    4.23  5069.3     5.3 5069.99    5.34  5070.1    5.35
  5071.7    5.46  5084.2    9.69  5086.5   10.47  5090.7   11.89  5100.4   15.17
  5123.1   15.63  5238.2   17.94  5238.8   22.25  5331.8   23.26  5331.9   23.27
  5340.4   19.89  5410.4   20.79  5455.4   20.09  5480.4   21.09  5500.4   22.49
  5525.4   23.09  5550.4   23.09  5575.4   25.39  5595.4   26.59  5765.6   28.49
BR D #Mann= 5
  4208.2      .2  4730.9      .1  4971.2    .045  5024.3      .1  5123.1      .2
BR D Banks=4971.2,5024.3
BC Design=,, 0 ,, 0 ,,,,,,
BC HTab HWMax=28.96
BC Use User HTab Curves=0
BC User HTab FreeFlow(D)= 0

Type RM Length L Ch R = 1 ,2007.2  ,39.5,39.5,39.5
BEGIN DESCRIPTION:
Downstream Section of Bridge/Culvert/Weir
END DESCRIPTION:
XS GIS Cut Line= 5
      3155019.16       13825036.      3154917.32     13824533.87
      3154748.92     13824353.92      3154709.77     13824311.87
      3154179.59     13823794.35
#Sta/Elev= 30
  4208.2   23.09  4313.2   20.89  4707.8   18.49  4730.9   15.19  4770.6    9.37
  4806.8    7.13  4855.7    4.59  4931.5    3.48  4945.1    1.03  4959.5    2.99
  4971.2    2.48  4976.6     .92  4977.9    -.89  4990.4   -6.94    4999   -7.98
  5013.5   -6.89  5022.1    -.56  5022.5    1.76  5024.3    2.02  5071.7    5.26
  5100.4   14.97  5123.1   15.43  5238.2   17.74  5238.8   22.05  5331.9   23.07
  5340.4   19.69  5455.4   19.89  5550.4   22.89  5595.4   26.39  5765.6   28.29
#Mann= 5 , 1 , 0
  4208.2      .2       0  4730.9      .1       0  4971.2    .045       0
  5024.3      .1       0  5123.1      .2       0
#XS Ineff= 2 , 0
       0    4747    13.2  5095.3       0    13.3
Permanent Ineff=
       F       F
Bank Sta=4971.2,5024.3
XS Rating Curve= 0 ,0
Exp/Cntr=0.5,0.3

Type RM Length L Ch R = 1 ,1967.7  ,22,22,22
BEGIN DESCRIPTION:
Upstream Section of Bridge/Culvert/Weir
END DESCRIPTION:
XS GIS Cut Line= 2
      3155280.07     13824926.53      3154274.73     13823756.79
#Sta/Elev= 30
  4208.4   23.29  4602.2   18.73  4671.5   17.25    4694   15.65  4709.7    16.9
    4740   14.17  4787.6   13.02    4807   10.85  4849.5    11.7  4881.3    8.77
  4890.3    6.21  4910.8    4.62 4978.77    3.32 4982.27   -2.32 4990.47   -8.54
 5002.57   -8.77 5013.67   -5.94 5024.07    4.09 5049.17    7.65 5065.97   14.75
  5184.7   18.13  5210.2   20.86  5247.8   21.75  5270.6   21.79  5313.6   19.67
  5420.9   19.09  5463.9   22.34  5570.5   23.57  5638.6   26.11  5750.8   27.41
#Mann= 5 , 1 , 0
  4208.4      .1       0 4978.77    .045       0 5024.07      .1       0
  5247.8     .08       0  5638.6      .2       0
#XS Ineff= 2 , 0
       0  4881.3     8.5  5050.9       0     8.1
Permanent Ineff=
       F       F
Bank Sta=4978.77,5024.07
XS Rating Curve= 0 ,0
Exp/Cntr=0.5,0.3

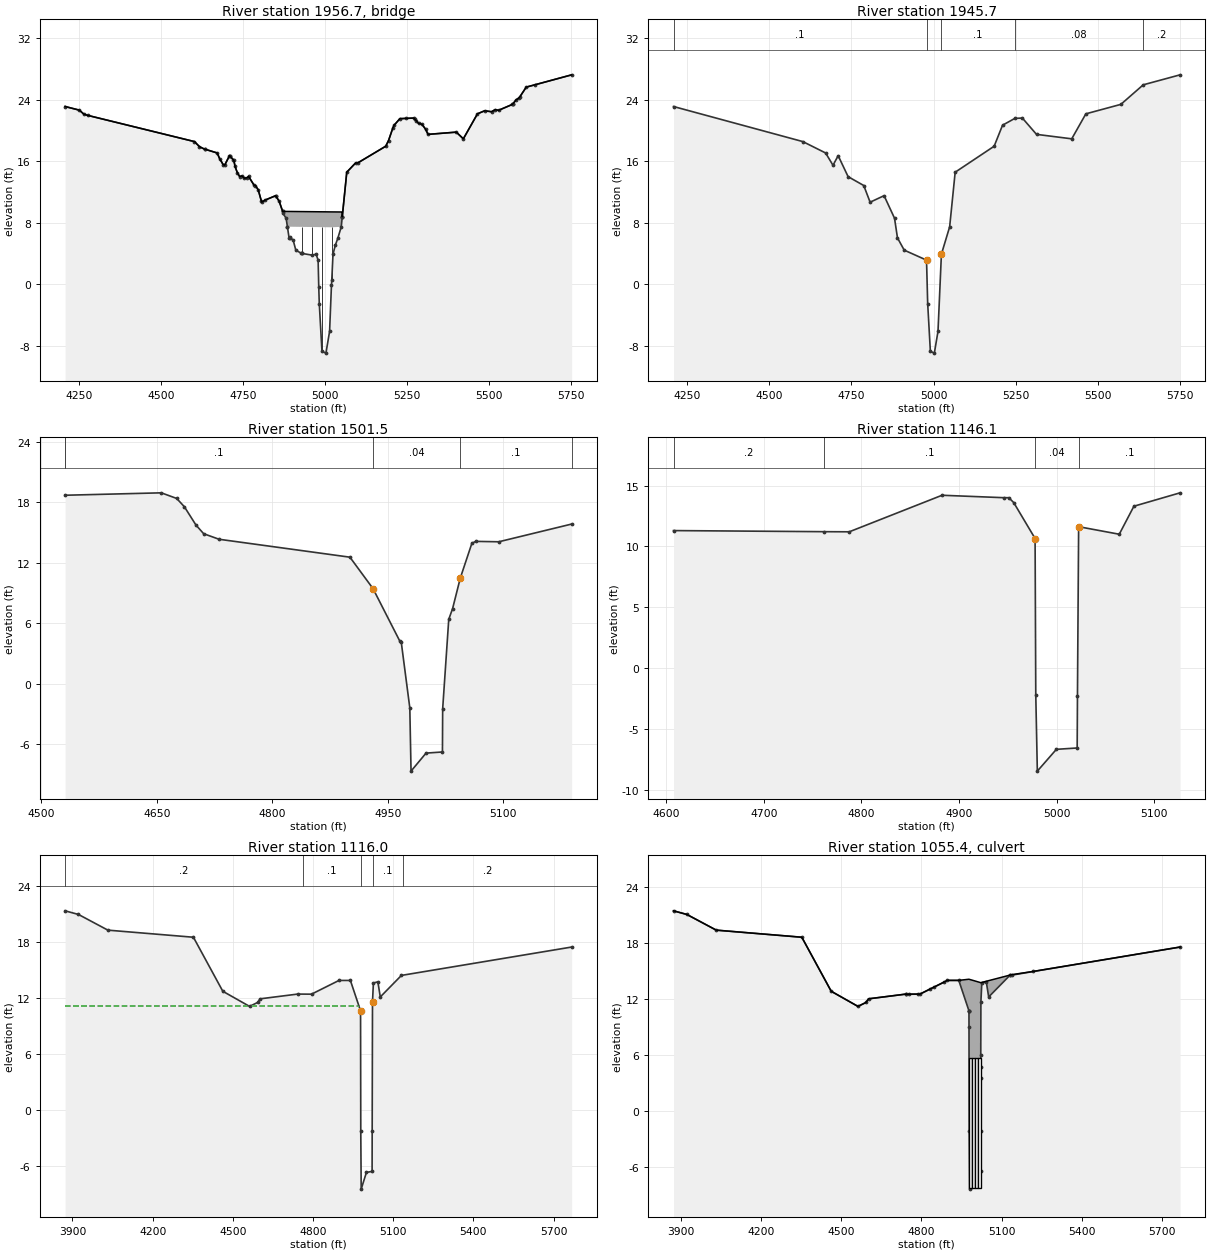
Type RM Length L Ch R = 3 ,1956.7  ,,,
BEGIN DESCRIPTION:
24" DIAMETER PIPELINE
END DESCRIPTION:
Bridge Culvert--1,0,-1,-1, 0
Deck Dist Width WeirC Skew NumUp NumDn MinLoCord MaxHiCord MaxSubmerge Is_Ogee
10,2,2.6,0, 60, 60, , , 0.95, 0, 1,1,,
  4208.4  4251.6  4265.5    4277  4602.2  4617.5  4632.8  4671.5  4678.7  4689.6
    4694  4709.3  4722.1  4725.9  4732.7    4740  4746.5    4754  4761.9    4767
  4783.9  4787.6  4796.4    4807  4817.6  4849.5  4860.1 4870.77  4871.7  4881.3
 4885.17 5019.37 5049.17 5052.17 5052.27 5065.97 5092.77 5098.77  5184.7  5193.2
  5206.2  5210.2  5227.7  5270.6  5284.5  5295.1  5305.7  5313.6  5399.5  5420.9
  5463.9    5486  5506.8  5517.8  5528.3  5570.5  5581.5  5591.4  5612.4  5750.8
   23.09   22.62    22.1   21.94   18.53   17.87   17.55   17.05   16.33   15.54
   15.45   16.71   16.09    15.3   14.49   13.97   14.07   13.78   13.82      14
   12.85   12.82   12.26   10.65   10.93    11.5   10.78    9.45    9.45    9.45
    9.45    9.39    9.38    9.38    8.76   14.55   15.75   15.74   17.93   18.67
   20.29   20.66   21.51   21.59    20.9   20.78   20.15   19.47   19.76   18.89
   22.14   22.54   22.41   22.68    22.6   23.37   23.95   24.24   25.61   27.21
   23.09   22.62    22.1   21.94   18.53   17.87   17.55   17.05   16.33   15.54
   15.45   16.71   16.09    15.3   14.49   13.97   14.07   13.78   13.82      14
   12.85   12.82   12.26   10.65   10.93    11.5   10.78    9.45    9.19    8.57
    7.47    7.39    7.45    8.72    8.76   14.55   15.75   15.74   17.93   18.67
   20.29   20.66   21.51   21.59    20.9   20.78   20.15   19.47   19.76   18.89
   22.14   22.54   22.41   22.68    22.6   23.37   23.95   24.24   25.61   27.21
  4208.4  4251.6  4265.5    4277  4602.2  4617.5  4632.8  4671.5  4678.7  4689.6
    4694  4709.3  4722.1  4725.9  4732.7    4740  4746.5    4754  4761.9    4767
  4783.9  4787.6  4796.4    4807  4817.6  4849.5  4860.1 4870.77  4871.7  4881.3
 4885.17 5019.37 5049.17 5052.17 5052.27 5065.97 5092.77 5098.77  5184.7  5193.2
  5206.2  5210.2  5227.7  5270.6  5284.5  5295.1  5305.7  5313.6  5399.5  5420.9
  5463.9    5486  5506.8  5517.8  5528.3  5570.5  5581.5  5591.4  5612.4  5750.8
   23.09   22.62    22.1   21.94   18.53   17.87   17.55   17.05   16.33   15.54
   15.45   16.71   16.09    15.3   14.49   13.97   14.07   13.78   13.82      14
   12.85   12.82   12.26   10.65   10.93    11.5   10.78    9.45    9.45    9.45
    9.45    9.39    9.38    9.38    8.76   14.55   15.75   15.74   17.93   18.67
   20.29   20.66   21.51   21.59    20.9   20.78   20.15   19.47   19.76   18.89
   22.14   22.54   22.41   22.68    22.6   23.37   23.95   24.24   25.61   27.21
   23.09   22.62    22.1   21.94   18.53   17.87   17.55   17.05   16.33   15.54
   15.45   16.71   16.09    15.3   14.49   13.97   14.07   13.78   13.82      14
   12.85   12.82   12.26   10.65   10.93    11.5   10.78    9.45    9.19    8.57
    7.47    7.39    7.45    8.72    8.76   14.55   15.75   15.74   17.93   18.67
   20.29   20.66   21.51   21.59    20.9   20.78   20.15   19.47   19.76   18.89
   22.14   22.54   22.41   22.68    22.6   23.37   23.95   24.24   25.61   27.21
Pier Skew, UpSta & Num, DnSta & Num=  ,4929.7, 2 ,4929.7, 2 , 0 , 0 , 0 ,,
     1.3     1.3
    2.99    8.43
     1.3     1.3
    2.99    8.43
Pier Skew, UpSta & Num, DnSta & Num=  ,4960.5, 2 ,4960.5, 2 , 0 , 0 , 0 ,,
     1.3     1.3
    2.77    8.42
     1.3     1.3
    2.77    8.42
Pier Skew, UpSta & Num, DnSta & Num=  ,4990.5, 2 ,4990.5, 2 , 0 , 0 , 0 ,,
     1.3     1.3
   -9.75    8.41
     1.3     1.3
   -9.75    8.41
Pier Skew, UpSta & Num, DnSta & Num=  ,5020.4, 2 ,5020.4, 2 , 0 , 0 , 0 ,,
     1.3     1.3
    -.88    8.39
     1.3     1.3
    -.88    8.39
BR Coef= 1 , 1 , 0 ,1.25, 0 ,,,0.8,0,2,0,
WSPro=,,,, 1 ,,,, 0 ,,,, 0 ,,,,-1 ,-1 ,-1 , 0 , 0 , 0 , 0 , 0
BR U #Sta/Elev= 96
  4208.4   23.09  4251.6   22.62  4265.5    22.1    4277   21.94  4602.2   18.53
  4617.5   17.87  4632.8   17.55  4633.3   17.56  4671.5   17.05  4678.7   16.33
  4689.6   15.54    4694   15.45  4708.8   16.71  4709.3   16.71  4709.7    16.7
  4720.8   16.13  4722.1   16.09  4725.9    15.3  4732.7   14.49    4740   13.97
  4746.5   14.07    4754   13.78  4761.9   13.82    4767      14  4783.9   12.85
  4787.6   12.82  4796.4   12.26  4805.8    10.8    4807   10.65  4817.6   10.93
  4849.5    11.5  4849.7   11.46  4860.1   10.78  4870.7    9.47 4870.77    9.45
  4871.7    9.19  4881.3    8.57 4885.08    7.49 4885.17    7.47  4890.3    6.01
  4891.9    6.09  4893.6    5.97  4902.5    5.76  4910.8    4.42 4926.67    4.03
 4929.67    3.99 4929.77    3.99 4960.47    3.77 4972.57    3.89 4978.77    3.12
 4980.67    -.38 4982.27   -2.52 4990.47   -8.74 5002.57   -8.97 5013.67   -6.14
 5019.37    -.13 5020.37     .57 5024.07    3.89 5031.07    5.05 5038.57    5.94
 5049.17    7.45 5052.06    8.67 5052.17    8.72 5052.27    8.76 5065.97   14.55
 5092.77   15.75 5098.77   15.74  5184.7   17.93  5193.2   18.67  5206.2   20.29
  5210.2   20.66  5227.7   21.51  5247.8   21.55  5270.6   21.59  5273.8   21.46
    5277   21.24  5284.5    20.9  5295.1   20.78  5305.7   20.15  5313.6   19.47
  5399.5   19.76  5420.9   18.89  5463.9   22.14    5486   22.54  5506.8   22.41
  5517.8   22.68  5528.3    22.6  5570.5   23.37  5570.9    23.4  5571.2   23.41
  5581.5   23.95  5591.4   24.24  5592.1    24.3  5612.4   25.61  5638.6   25.91
  5750.8   27.21
BR U #Mann= 5
  4208.4      .1 4978.77    .045 5024.07      .1  5247.8     .08  5638.6      .2
BR U Banks=4978.77,5024.07
BR D #Sta/Elev= 96
  4208.4   23.09  4251.6   22.62  4265.5    22.1    4277   21.94  4602.2   18.53
  4617.5   17.87  4632.8   17.55  4633.3   17.56  4671.5   17.05  4678.7   16.33
  4689.6   15.54    4694   15.45  4708.8   16.71  4709.3   16.71  4709.7    16.7
  4720.8   16.13  4722.1   16.09  4725.9    15.3  4732.7   14.49    4740   13.97
  4746.5   14.07    4754   13.78  4761.9   13.82    4767      14  4783.9   12.85
  4787.6   12.82  4796.4   12.26  4805.8    10.8    4807   10.65  4817.6   10.93
  4849.5    11.5  4849.7   11.46  4860.1   10.78  4870.7    9.47 4870.77    9.45
  4871.7    9.19  4881.3    8.57 4885.08    7.49 4885.17    7.47  4890.3    6.01
  4891.9    6.09  4893.6    5.97  4902.5    5.76  4910.8    4.42 4926.67    4.03
 4929.67    3.99 4929.77    3.99 4960.47    3.77 4972.57    3.89 4978.77    3.12
 4980.67    -.38 4982.27   -2.52 4990.47   -8.74 5002.57   -8.97 5013.67   -6.14
 5019.37    -.13 5020.37     .57 5024.07    3.89 5031.07    5.05 5038.57    5.94
 5049.17    7.45 5052.06    8.67 5052.17    8.72 5052.27    8.76 5065.97   14.55
 5092.77   15.75 5098.77   15.74  5184.7   17.93  5193.2   18.67  5206.2   20.29
  5210.2   20.66  5227.7   21.51  5247.8   21.55  5270.6   21.59  5273.8   21.46
    5277   21.24  5284.5    20.9  5295.1   20.78  5305.7   20.15  5313.6   19.47
  5399.5   19.76  5420.9   18.89  5463.9   22.14    5486   22.54  5506.8   22.41
  5517.8   22.68  5528.3    22.6  5570.5   23.37  5570.9    23.4  5571.2   23.41
  5581.5   23.95  5591.4   24.24  5592.1    24.3  5612.4   25.61  5638.6   25.91
  5750.8   27.21
BR D #Mann= 5
  4208.4      .1 4978.77    .045 5024.07      .1  5247.8     .08  5638.6      .2
BR D Banks=4978.77,5024.07
BC Design=,, 0 ,, 0 ,,,,,,
BC HTab HWMax=27.41
BC Use User HTab Curves=0
BC User HTab FreeFlow(D)= 0

Type RM Length L Ch R = 1 ,1945.7  ,444.2,444.2,444.2
BEGIN DESCRIPTION:
Downstream Section of Bridge/Culvert/Weir
END DESCRIPTION:
XS GIS Cut Line= 2
        3155302.     13824924.77      3154296.66     13823755.04
#Sta/Elev= 30
  4208.4    23.1  4602.2   18.54  4671.5   17.06    4694   15.46  4709.7   16.71
    4740   13.98  4787.6   12.83    4807   10.66  4849.5   11.51  4881.3    8.58
  4890.3    6.02  4910.8    4.43 4978.77    3.13 4982.27   -2.51 4990.47   -8.73
 5002.57   -8.96 5013.67   -6.13 5024.07     3.9 5049.17    7.46 5065.97   14.56
  5184.7   17.94  5210.2   20.67  5247.8   21.56  5270.6    21.6  5313.6   19.48
  5420.9    18.9  5463.9   22.15  5570.5   23.38  5638.6   25.92  5750.8   27.22
#Mann= 5 , 1 , 0
  4208.4      .1       0 4978.77    .045       0 5024.07      .1       0
  5247.8     .08       0  5638.6      .2       0
#XS Ineff= 2 , 0
       0  4881.3     8.5  5050.9       0     8.1
Permanent Ineff=
       F       F
Bank Sta=4978.77,5024.07
XS Rating Curve= 0 ,0
Exp/Cntr=0.5,0.3

Type RM Length L Ch R = 1 ,1501.5  ,350.1,355.4,360
BEGIN DESCRIPTION:
Cross Section 1501.5-Interpolated
END DESCRIPTION:
XS GIS Cut Line= 4
      3155361.29     13824725.09      3155235.28     13824306.97
      3155212.37     13824249.69      3155172.27     13824095.05
#Sta/Elev= 23
  4530.8   18.71  4655.8   18.95  4675.8   18.39  4685.8   17.56  4700.8   15.75
  4710.8   14.89  4730.8   14.34  4900.8   12.56  4930.8    9.44  4965.8     4.2
  4967.5    4.12  4978.6    -2.4  4980.2   -8.68  4999.7   -6.89    5021   -6.78
  5021.3   -2.49  5029.2    6.39  5034.2    7.46  5044.2   10.49  5059.2   13.93
  5064.2   14.13  5094.2   14.09  5188.9   15.85
#Mann= 5 , 1 , 0
  4530.8      .2       0  4530.8      .1       0  4930.8     .04       0
  5044.2      .1       0  5188.9      .2       0
Bank Sta=4930.8,5044.2
XS Rating Curve= 0 ,0
Exp/Cntr=0.3,0.1

Type RM Length L Ch R = 1 ,1146.1  ,29.6,30.1,33.7
BEGIN DESCRIPTION:
Cross Section 1146.1-Interpolated
END DESCRIPTION:
XS GIS Cut Line= 5
      3155608.77     13824581.63      3155576.61     13824244.79
      3155568.15     13824192.32      3155546.14      13824104.3
      3155537.68     13824068.76
#Sta/Elev= 17
  4607.6    11.3  4761.4   11.21  4787.6    11.2  4882.6    14.2    4946      14
    4951      14    4956    13.6  4977.9   10.65  4978.6   -2.17  4980.2   -8.45
  4999.7   -6.66    5021   -6.55  5021.3   -2.26  5022.5   11.62  5064.1      11
  5079.1    13.3  5126.4    14.4
#Mann= 4 , 1 , 0
  4607.6      .2       0  4761.4      .1       0  4977.9     .04       0
  5022.5      .1       0
Bank Sta=4977.9,5022.5
XS Rating Curve= 0 ,0
Exp/Cntr=0.5,0.3

Type RM Length L Ch R = 1 ,1116.0  ,121.2,121.2,121.2
BEGIN DESCRIPTION:
Upstream Section of Bridge/Culvert/Weir
END DESCRIPTION:
XS GIS Cut Line= 5
      3155665.14     13825308.47        3155639.     13824403.88
      3155613.06     13824220.92      3155605.58     13824168.15
      3155500.05     13823423.45
#Sta/Elev= 25
  3872.5   21.39  3922.5      21  4032.5   19.32  4352.5   18.56  4462.5   12.77
  4562.5   11.15  4592.5   11.57    4602   11.96  4742.6   12.47  4794.3   12.46
    4897   13.93  4939.8   13.93  4977.7   10.68  4977.8   10.67  4978.6   -2.15
  4980.2   -8.43  4999.7   -6.64    5021   -6.53  5021.3   -2.24  5022.5   11.64
  5025.9   13.66  5042.6   13.78  5051.6   12.16  5130.7   14.47  5767.7   17.51
#Mann= 5 , 1 , 0
  3872.5      .2       0  4761.4      .1       0  4977.7     .04       0
  5022.5      .1       0  5137.9      .2       0
#XS Ineff= 2 , 0
       0    4973    11.2  5031.5       0    13.7
Permanent Ineff=
       F       F
Bank Sta=4977.7,5022.5
XS Rating Curve= 0 ,0
Exp/Cntr=0.5,0.3

Type RM Length L Ch R = 2 ,1055.4  ,,,
BEGIN DESCRIPTION:
STATE ROUTE 225 ACCESS ROAD
Structure ID: C02-1
END DESCRIPTION:
Bridge Culvert--1,0,-1,-1, 0
Deck Dist Width WeirC Skew NumUp NumDn MinLoCord MaxHiCord MaxSubmerge Is_Ogee
10,101.2,3,0, 39, 39, , , 0.95, 0, 1,1,,
  3872.5  3922.5  4032.5  4352.5  4462.5  4562.5  4592.5    4602  4742.6  4742.9
  4754.9  4785.9  4794.3  4832.9  4845.6  4885.5    4897  4939.8 4977.59  4977.7
  4977.8 4977.91  4978.6  4980.2  4999.7    5021  5021.3 5021.79  5021.9 5022.01
  5022.5  5025.9  5042.6  5051.6  5130.7  5133.1  5138.1  5218.9  5767.7
    21.4   21.01   19.33   18.57   12.78   11.16   11.58   11.97   12.48   12.46
   12.47   12.48   12.48   13.03   13.21   13.78   13.95   13.95   14.07   14.07
   14.07   14.07   14.06   14.05   13.89   13.71    13.7    13.7    13.7    13.7
    13.7   13.73   13.85   13.92   14.51   14.52   14.56   14.91   17.52
    21.4   21.01   19.33   18.57   12.78   11.16   11.58   11.97   12.48   12.46
   12.46   12.47   12.47   13.02    13.2   13.77   13.94   13.94    10.7   10.69
   10.68    8.92   -2.14   -8.42   -6.63   -6.52   -2.23    3.44    4.71    5.98
   11.65   13.67   13.79   12.17   14.48   14.49   14.51    14.9   17.52
  3872.5  3922.5  4032.5  4352.5  4462.5  4562.5  4592.5    4602  4742.6  4742.9
  4754.9  4785.9  4794.3  4832.9  4845.6  4885.5    4897  4939.8 4977.59  4977.7
  4977.8 4977.91  4978.6  4980.2  4999.7    5021  5021.3 5021.79  5021.9 5022.01
  5022.5  5025.9  5042.6  5051.6  5130.7  5133.1  5138.1  5218.9  5767.7
    21.4   21.01   19.33   18.57   12.78   11.16   11.58   11.97   12.48   12.46
   12.47   12.48   12.48   13.03   13.21   13.78   13.95   13.95   14.07   14.07
   14.07   14.07   14.06   14.05   13.89   13.71    13.7    13.7    13.7    13.7
    13.7   13.73   13.85   13.92   14.51   14.52   14.56   14.91   17.52
   21.34   20.95   19.27   18.51   12.72    11.1   11.52   11.91   12.42    12.4
    12.4   12.41   12.41   12.96   13.14   13.71   13.88   13.88   10.64   10.63
   10.62    8.86    -2.2   -8.48   -6.69   -6.58   -2.29    3.38    4.65    5.92
   11.59   13.61   13.73   12.11   14.42   14.43   14.45   14.84   17.46
BR Coef= 1 , 0 , 0 ,1.25, 0 ,,,0.8,-1,2,0,
WSPro=,,,, 1 ,,,, 0 ,,,, 0 ,,,,-1 ,-1 ,-1 , 0 , 0 , 0 , 0 , 0
Culvert=2,14,10,101.2,0.02,0.4,1,8,1,-8.34,4983.4,-8.48,4983.4,Culvert #1  , 0 ,10
Culvert Bottom n=0.02
Culvert=2,14,10,101.2,0.02,0.4,1,8,1,-8.34,4994.4,-8.48,4994.4,Culvert #2  , 0 ,10
Culvert Bottom n=0.02
Culvert=2,14,10,101.2,0.02,0.4,1,8,1,-8.34,5005.4,-8.48,5005.4,Culvert #3  , 0 ,10
Culvert Bottom n=0.02
Culvert=2,14,10,101.2,0.02,0.4,1,8,1,-8.34,5016.4,-8.48,5016.4,Culvert #4  , 0 ,10
Culvert Bottom n=0.02
BR U #Sta/Elev= 39
  3872.5    21.4  3922.5   21.01  4032.5   19.33  4352.5   18.57  4462.5   12.78
  4562.5   11.16  4592.5   11.58    4602   11.97  4742.6   12.48  4742.9   12.46
  4754.9   12.46  4785.9   12.47  4794.3   12.47  4832.9   13.02  4845.6    13.2
  4885.5   13.77    4897   13.94  4939.8   13.94 4977.59    10.7  4977.7   10.69
  4977.8   10.68 4977.91    8.92  4978.6   -2.14  4980.2   -8.42  4999.7   -6.63
    5021   -6.52  5021.3   -2.23 5021.79    3.44  5021.9    4.71 5022.01    5.98
  5022.5   11.65  5025.9   13.67  5042.6   13.79  5051.6   12.17  5130.7   14.48
  5133.1   14.49  5138.1   14.51  5218.9    14.9  5767.7   17.52
BR U #Mann= 5
  3872.5      .2  4761.4      .1  4977.7     .04  5022.5      .1  5137.9      .2
BR U Banks=4977.7,5022.5
BR D #Sta/Elev= 39
  3872.5   21.34  3922.5   20.95  4032.5   19.27  4352.5   18.51  4462.5   12.72
  4562.5    11.1  4592.5   11.52    4602   11.91  4742.6   12.42  4742.9    12.4
  4754.9    12.4  4785.9   12.41  4794.3   12.41  4832.9   12.96  4845.6   13.14
  4885.5   13.71    4897   13.88  4939.8   13.88 4977.59   10.64  4977.7   10.63
  4977.8   10.62 4977.91    8.86  4978.6    -2.2  4980.2   -8.48  4999.7   -6.69
    5021   -6.58  5021.3   -2.29 5021.79    3.38  5021.9    4.65 5022.01    5.92
  5022.5   11.59  5025.9   13.61  5042.6   13.73  5051.6   12.11  5130.7   14.42
  5133.1   14.43  5138.1   14.45  5218.9   14.84  5767.7   17.46
BR D #Mann= 5
  3872.5      .2  4761.4      .1  4977.7     .04  5022.5      .1  5137.9      .2
BR D Banks=4977.7,5022.5
BC Design=,, 0 ,, 0 ,,,,,,
BC HTab HWMax=21.39
BC Use User HTab Curves=0
BC User HTab FreeFlow(D)= 0

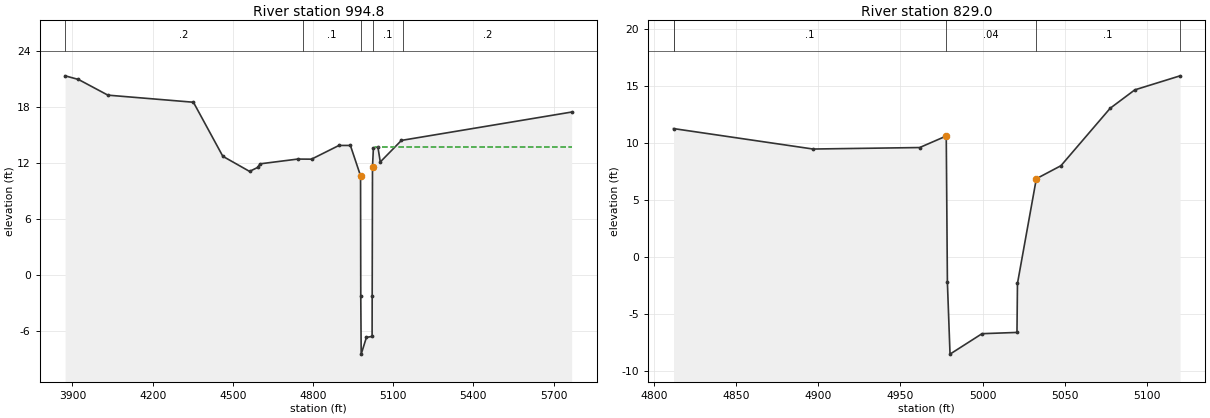
Type RM Length L Ch R = 1 ,994.8   ,165.8,165.8,165.8
BEGIN DESCRIPTION:
Downstream Section of Bridge/Culvert/Weir
END DESCRIPTION:
XS GIS Cut Line= 5
      3155785.42     13825293.59      3155759.28       13824389.
      3155733.34     13824206.04      3155725.86     13824153.27
      3155620.33     13823408.57
#Sta/Elev= 25
  3872.5   21.34  3922.5   20.95  4032.5   19.27  4352.5   18.51  4462.5   12.72
  4562.5    11.1  4592.5   11.52    4602   11.91  4742.6   12.42  4794.3   12.41
    4897   13.88  4939.8   13.88  4977.7   10.63  4977.8   10.62  4978.6    -2.2
  4980.2   -8.48  4999.7   -6.69    5021   -6.58  5021.3   -2.29  5022.5   11.59
  5025.9   13.61  5042.6   13.73  5051.6   12.11  5130.7   14.42  5767.7   17.46
#Mann= 5 , 1 , 0
  3872.5      .2       0  4761.4      .1       0  4977.7     .04       0
  5022.5      .1       0  5137.9      .2       0
#XS Ineff= 2 , 0
       0    4973      11  5031.5       0    13.7
Permanent Ineff=
       F       F
Bank Sta=4977.7,5022.5
XS Rating Curve= 0 ,0
Exp/Cntr=0.5,0.3

Type RM Length L Ch R = 1 ,829.0   ,0,0,0
BEGIN DESCRIPTION:
Cross Section 829.0-Interpolated
END DESCRIPTION:
XS GIS Cut Line= 4
      3155888.09     13824350.27      3155883.13      13824172.1
      3155882.51     13824134.24       3155879.4     13824041.74
#Sta/Elev= 14
  4811.7   11.25  4896.7    9.46  4961.7    9.59  4977.9    10.6  4978.6   -2.22
  4980.2    -8.5  4999.7   -6.71    5021    -6.6  5021.3   -2.31  5032.8    6.86
  5047.8       8  5077.8   13.03  5092.8   14.64  5120.4   15.87
#Mann= 5 , 1 , 0
  4811.7      .2       0  4811.7      .1       0  4977.9     .04       0
  5032.8      .1       0  5120.4      .2       0
Bank Sta=4977.9,5032.8
XS Rating Curve= 0 ,0
Exp/Cntr=0.3,0.1

Chan Stop Cuts=-1
Use User Specified Reach Order=0
Composite Channel Slope=5